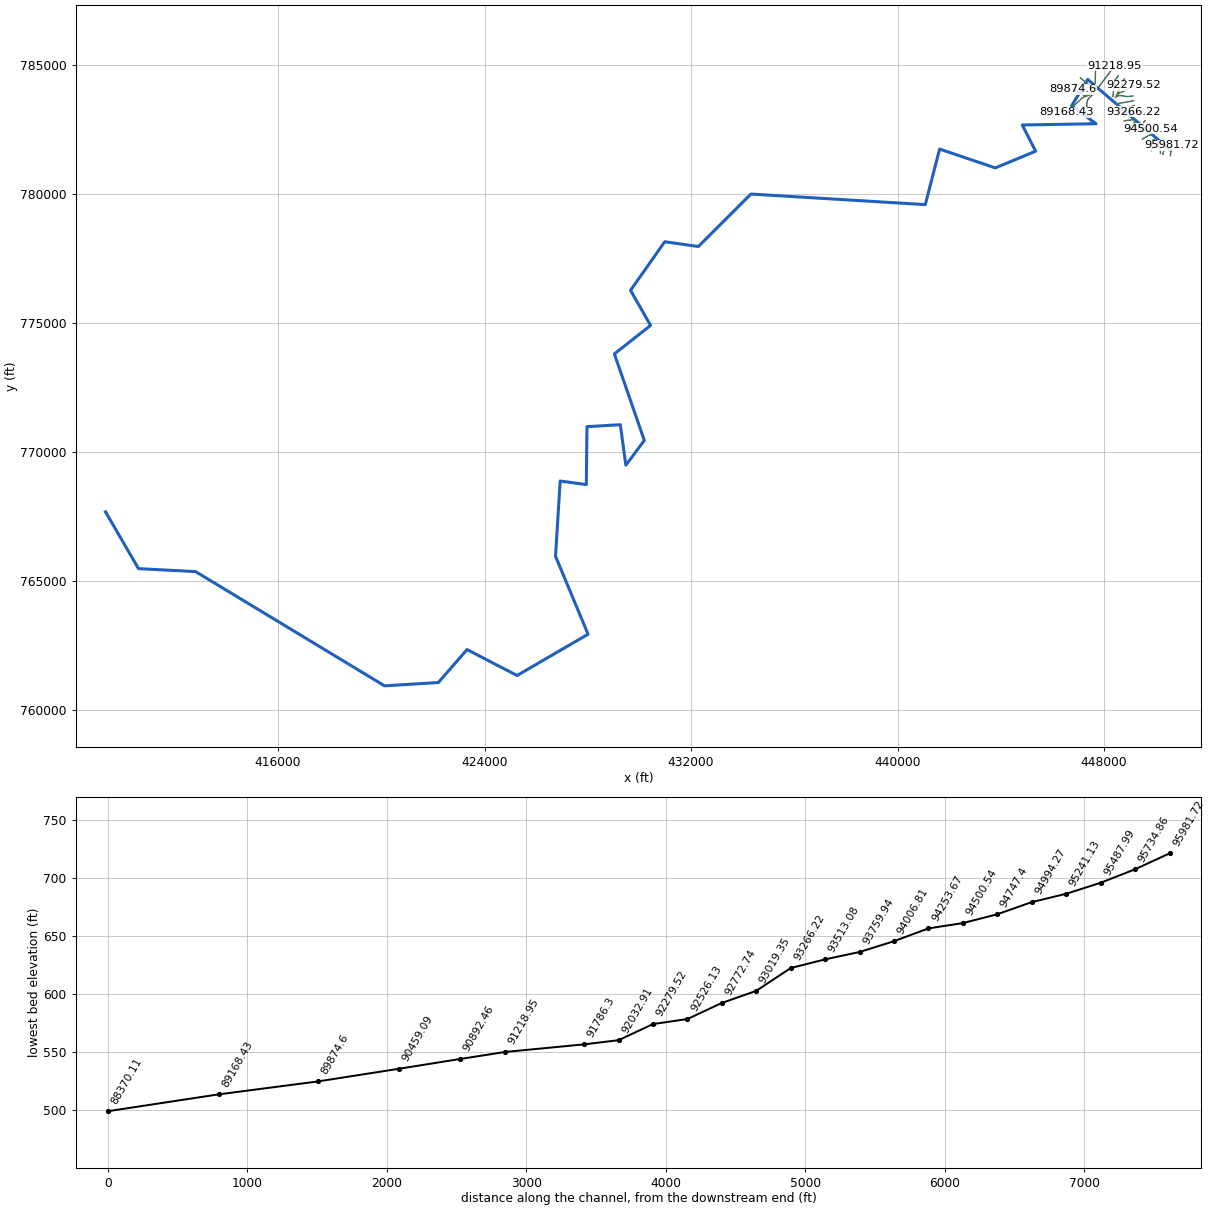
--- 2953_ras.prj (project) ---

Proj Title=2953
Current Plan=p01
Default Exp/Contr=0.3,0.1
English Units
Geom File=g01
Flow File=f01
Plan File=p01
Y Axis Title=Elevation
X Axis Title(PF)=Main Channel Distance
X Axis Title(XS)=Station
BEGIN DESCRIPTION:
RFD model 2953 exported to HEC-RAS
END DESCRIPTION:

--- 2953_ras.p01 (plan) ---

Plan Title=Plan 01
Program Version=4.10
Short Identifier=Plan 01
Geom File=g01
Flow File=f01
Subcritical Flow
Calc Critical at every XS
Secant Critical Depth

--- 2953_ras.f01 (steady flow) ---

Flow Title=Flow 01
Program Version=5.01
Number of Profiles= 6
Profile Names=10yr,25yr,50yr,100yr,100plus,500yr
River Rch & RM=2953,118,95981.72
 2632.23 3992.42 5217.25 6236.08 9104.6810086.76
River Rch & RM=2953,118,95734.86
 2656.49  4030.8  5268.8 6299.13 9196.7310179.36
River Rch & RM=2953,118,95487.99
 2661.43 4038.68 5279.41 6312.17 9215.7610198.66
River Rch & RM=2953,118,95241.13
 2668.75 4050.31 5295.09  6331.4 9243.8410227.06
River Rch & RM=2953,118,94994.27
    2696  4093.6 5353.37 6402.84 9348.15 10332.3
River Rch & RM=2953,118, 94747.4
 2699.36 4098.95  5360.6 6411.71  9361.110345.43
River Rch & RM=2953,118,94500.54
    2726 4141.27 5417.59 6481.58 9463.1110448.18
River Rch & RM=2953,118,94253.67
 2732.44 4151.54 5431.44  6498.6 9487.9610473.31
River Rch & RM=2953,118,94006.81
 2740.41 4164.25  5448.6 6519.68 9518.7410504.43
River Rch & RM=2953,118,93759.94
 2750.11 4179.75 5469.55 6545.45 9556.3510542.53
River Rch & RM=2953,118,93513.08
 2751.65 4182.21 5472.87 6549.52 9562.3110548.54
River Rch & RM=2953,118,93266.22
 2755.94 4189.09 5482.18    6561 9579.0510565.56
River Rch & RM=2953,118,93019.35
 2761.23 4197.57 5493.68 6575.16 9599.7310586.58
River Rch & RM=2953,118,92772.74
 2764.74  4203.2 5501.31 6584.57 9613.4710600.58
River Rch & RM=2953,118,92526.13
 2768.02 4208.46 5508.43 6593.34 9626.2710613.57
River Rch & RM=2953,118,92279.52
 2782.32  4231.3 5539.27 6631.25 9681.6210669.47
River Rch & RM=2953,118,92032.91
 2783.32  4232.9 5541.44 6633.93 9685.5310673.46
River Rch & RM=2953,118, 91786.3
 9020.5913781.6818115.0421726.2831720.3729644.06
River Rch & RM=2953,118,91218.95
 9034.6713804.4718146.1421764.7831776.5829692.78
River Rch & RM=2953,118,90892.46
 9512.2714570.2419184.63 23043.633643.6531283.99
River Rch & RM=2953,118,90459.09
 9515.2814575.1419191.31 23051.933655.7731294.45
River Rch & RM=2953,118, 89874.6
 9537.6114611.55 19241.223113.8733746.2431372.83
River Rch & RM=2953,118,89168.43
 9713.4414894.4319625.6623588.2134438.7931962.16
River Rch & RM=2953,118,88370.11
 9556.1314641.6919282.4523165.07   3382131437.44
River Rch & RM=2953,118,87882.09
 9563.3314653.3619298.3923184.8133849.8331462.22
River Rch & RM=2953,118,87394.06
 9574.3714671.2419322.7723214.9933893.8831500.04
River Rch & RM=2953,118,86906.03
 9607.6814725.0619396.1123305.6834026.2931613.38
River Rch & RM=2953,118,86418.01
 9711.7514891.6919621.9223583.5734432.0131956.32
River Rch & RM=2953,118,85929.98
 9743.0714942.1919690.6423668.4634555.95 32061.9
River Rch & RM=2953,118,85441.95
 9756.3114963.6419719.9123704.6934608.85 32107.2
River Rch & RM=2953,118,84953.93
 9790.0215018.3919794.7523797.4934744.3332223.57
River Rch & RM=2953,118, 84465.9
  9799.215033.2919815.1223822.7534781.2132255.22
River Rch & RM=2953,118,83893.21
 9811.1915052.7619841.7323855.7334829.3632296.54
River Rch & RM=2953,118,83489.85
 9990.6215344.1620240.04 24349.635550.4232914.52
River Rch & RM=2953,118,83001.82
  9995.115351.4320249.9724361.9135568.3932929.89
River Rch & RM=2953,118, 82529.1
10005.5815368.4320273.1924390.6835610.3932965.76
River Rch & RM=2953,118,82025.77
10066.3215466.3820406.5424555.4435850.9533169.76
River Rch & RM=2953,118,81537.74
10072.6915476.7120420.6324572.8935876.4333191.48
River Rch & RM=2953,118,81049.72
10085.2315497.1220448.5724607.5835927.0733234.89
River Rch & RM=2953,118,80561.69
10114.7715545.2720514.5424689.5436046.7333337.58
River Rch & RM=2953,118,80073.66
10127.89 15566.720543.9324726.0936100.0933383.46
River Rch & RM=2953,118,79585.64
10138.9515584.7920568.77   2475736145.2233422.32
River Rch & RM=2953,118,79183.71
10152.0115606.1520598.0824793.4736198.4733468.16
River Rch & RM=2953,118,78781.77
10155.6215612.06 20606.224803.5836213.2333480.89
River Rch & RM=2953,118,78379.84
10163.8715625.5820624.8124826.78 36247.133510.16
River Rch & RM=2953,118,77977.91
10180.4815652.7820662.1624873.29   3631533568.67
River Rch & RM=2953,118,77133.19
10230.9815735.3720775.5325014.3836520.9933745.86
River Rch & RM=2953,118,76690.39
10241.6715752.9320799.7125044.5436565.0233783.92
River Rch & RM=2953,118, 76247.6
10255.7115776.0220831.49 25084.236622.93   33834
River Rch & RM=2953,118, 75804.8
10963.7316902.47 22352.526950.0239347.0336084.07
River Rch & RM=2953,118, 75193.4
10971.4616915.1622369.97 26971.839378.8336111.26
River Rch & RM=2953,118, 74013.4
11106.7117137.0122675.1227352.2239934.2536585.11
River Rch & RM=2953,118,73139.32
 11198.417287.1722881.4827609.2940309.5736904.16
River Rch & RM=2953,118,72702.28
11200.8217291.1522886.9727616.1540319.5836912.74
River Rch & RM=2953,118,72265.24
11237.3717351.4722970.2627720.3240471.6637043.11
River Rch & RM=2953,118,71644.44
11260.3717389.4323022.6527785.8340567.3137125.03
River Rch & RM=2953,118,69990.13
11339.81 17520.923204.4828013.5440899.7737410.59
River Rch & RM=2953,118,69540.05
11799.7318269.2424229.1129285.89 42757.438968.61
River Rch & RM=2953,118,69089.97
11806.12 18279.824243.7229304.1942784.1238991.39
River Rch & RM=2953,118,68639.89
11822.5718307.0224281.3629351.3442852.9639050.11
River Rch & RM=2953,118,68189.81
11828.6218317.0424295.2129368.6842878.2739071.68
River Rch & RM=2953,118,67739.73
11837.7818332.2224316.2329395.0542916.7739104.61
River Rch & RM=2953,118,67289.65
11860.4318369.9624368.63 29460.943012.9139187.21
River Rch & RM=2953,118,66839.57
11881.3118404.6324416.69 29521.243100.9539262.56
River Rch & RM=2953,118,66360.96
11899.16 18434.324457.8229572.8343176.33 39327.1
River Rch & RM=2953,118,65882.36
11908.9418450.62 24480.529601.3643217.9939362.94
River Rch & RM=2953,118,65403.75
11916.4518463.13 24497.929623.2543249.9439390.41
River Rch & RM=2953,118,64925.15
12188.0518908.4825110.5930387.2244365.3440328.77
River Rch & RM=2953,118,64446.54
12466.7419371.58 25752.831193.5245542.5441331.29
River Rch & RM=2953,118,63967.94
12477.0919388.9925777.1331224.2445587.3941369.95
River Rch & RM=2953,118,63489.33
12491.1619412.6825810.2331266.0845648.4741422.64
River Rch & RM=2953,118,63010.73
12503.3519433.3825839.2931302.94 45702.341469.47
River Rch & RM=2953,118,62532.12
12576.5519555.7126009.5431517.3346015.31 41737.1
River Rch & RM=2953,118,62053.52
12581.2419563.95 26021.331532.4846037.4241756.94
River Rch & RM=2953,118,61574.92
12613.1519619.0426099.3831632.3246183.1941885.82
River Rch & RM=2953,118,61188.63
12618.6119628.6326113.1331650.0546209.0741909.13
River Rch & RM=2953,118,60617.71
12646.0119675.5326179.29 31734.346332.0842016.88
River Rch & RM=2953,118,59835.38
12658.3419697.0326209.9131773.63 46389.542068.09
River Rch & RM=2953,118,59137.85
 12701.319771.0126314.63 31907.446584.8142240.16
River Rch & RM=2953,118,57887.94
12879.5920075.0526742.7132451.8147379.6442932.68
River Rch & RM=2953,118, 56935.3
 12894.520102.1726782.2632503.5547455.1943002.49
River Rch & RM=2953,118,56178.13
12900.1520112.6426797.6532523.8147484.7743030.18
River Rch & RM=2953,118,55384.16
12906.8420125.0326815.8832547.8247519.8243063.04
River Rch & RM=2953,118,55042.37
12908.01 20127.226819.0832552.0447525.98 43068.8
River Rch & RM=2953,118,54243.43
13355.8120928.3727977.4234057.5949724.0945066.68
River Rch & RM=2953,118,53296.16
13372.1620958.9328022.62 34117.449811.4145148.76
River Rch & RM=2953,118, 52348.9
13528.7721243.73 28438.134661.4250605.6745878.71
River Rch & RM=2953,118,51744.59
13550.2921284.4328498.6534741.9350723.22   45990
River Rch & RM=2953,118,50622.25
13590.2621360.3828611.9434892.8750943.5946199.36
River Rch & RM=2953,118,50065.56
13596.2521371.8428629.11 34915.850977.0746231.32
River Rch & RM=2953,118,48693.52
13678.1921529.3728865.4435232.0451438.77 46673.4
River Rch & RM=2953,118,46665.31
13695.9421563.29 28916.235299.8351537.7546767.76
River Rch & RM=2953,118,45718.05
13712.3621594.4828962.7335361.8451628.2946853.68
River Rch & RM=2953,118,44770.78
13720.2921609.58 28985.335391.9551672.25 46895.5
River Rch & RM=2953,118,43823.52
13902.0221949.3229488.32 36058.552645.4147807.47
River Rch & RM=2953,118,42876.25
13925.9821995.1729556.9936150.3352779.4847935.21
River Rch & RM=2953,118,41805.52
 13934.922012.2329582.54 36184.552829.3847982.74
River Rch & RM=2953,118,40473.47
13951.2722043.5529629.4736247.2552920.9948070.01
River Rch & RM=2953,118,39561.03
13963.7522067.5529665.5136295.5252991.4548137.35
River Rch & RM=2953,118,38570.99
14008.7822154.1329795.5436469.7453245.8248380.46
River Rch & RM=2953,118,37211.91
14021.0222177.7529831.0636517.3953315.3948447.08
River Rch & RM=2953,118,35908.86
14040.2722214.9229887.0136592.4953425.0448552.17
River Rch & RM=2953,118,33893.97
14127.8922383.8830141.1436933.4553922.8449028.62
River Rch & RM=2953,118,32741.88
14280.0122677.6430583.5137527.5554790.2349859.15
River Rch & RM=2953,118,32562.05
14284.1222685.5730595.4237543.5454813.5749881.46
River Rch & RM=2953,118,31149.73
14294.9722706.4530626.8337585.68 54875.149940.22
River Rch & RM=2953,118,28747.58
14316.3322747.3530688.1937667.8754995.0950054.39
River Rch & RM=2953,118,25833.52
 14401.622909.9730931.6837993.5455470.5750505.18
River Rch & RM=2953,118,23179.28
14483.5823066.4231166.0438307.1655928.4550939.28
River Rch & RM=2953,118,19705.56
14509.39 23115.231238.7838404.1656070.0751072.52
River Rch & RM=2953,118,17884.19
14826.7523715.2532133.9939598.6757814.0652712.01
River Rch & RM=2953,118, 13275.9
14848.8823757.3432196.9839682.9357937.0952828.04
River Rch & RM=2953,118,8529.917
14898.5223852.6332340.2939875.3658218.0353094.86
River Rch & RM=2953,118,5187.372
14898.81 23853.232341.1439876.51 58219.753096.45
Boundary for River Rch & Prof#=2953,118,1
Up Type= 0
Dn Type= 2
Boundary for River Rch & Prof#=2953,118,2
Up Type= 0
Dn Type= 2
Boundary for River Rch & Prof#=2953,118,2
Up Type= 0
Dn Type= 2
Boundary for River Rch & Prof#=2953,118,2
Up Type= 0
Dn Type= 2
Boundary for River Rch & Prof#=2953,118,2
Up Type= 0
Dn Type= 2
Boundary for River Rch & Prof#=2953,118,2
Up Type= 0
Dn Type= 2

--- 2953_ras.g01 (geometry) ---

Geom Title=2953
Program Version=4.10

River Reach=2953,118
Reach XY= 30
  450583.8821069781680.282259256447366.312662363784429.448925942
 446742.28488487783408.337814823447688.726062417782713.752898097
444832.137865424782666.209559739445349.269838333 781650.60633336
443786.769838303781003.523000047441629.680599898781732.711119264
441074.408727169779581.578555509434320.311505139779990.398000017
432284.845472455777957.863022745430981.422616065778142.898000062
429657.255949408776260.398000017430432.327875316774902.268053621
429030.867060512773796.925777748430190.450394005770445.502167016
429474.660187244769488.201440886429261.630949408771054.877166644
427969.130949885770979.738277793427943.575394064768735.293833435
426930.389627218768873.618191093426750.924930871  765958.5692963
 428010.92493096762939.958185196425263.702708662761340.513740718
  423321.5499309762344.263740733422211.133264661761068.013740763
420127.799931169760940.097074091412807.084616393765365.125400633
410595.950357169765479.407808051409320.394801617767677.741141915

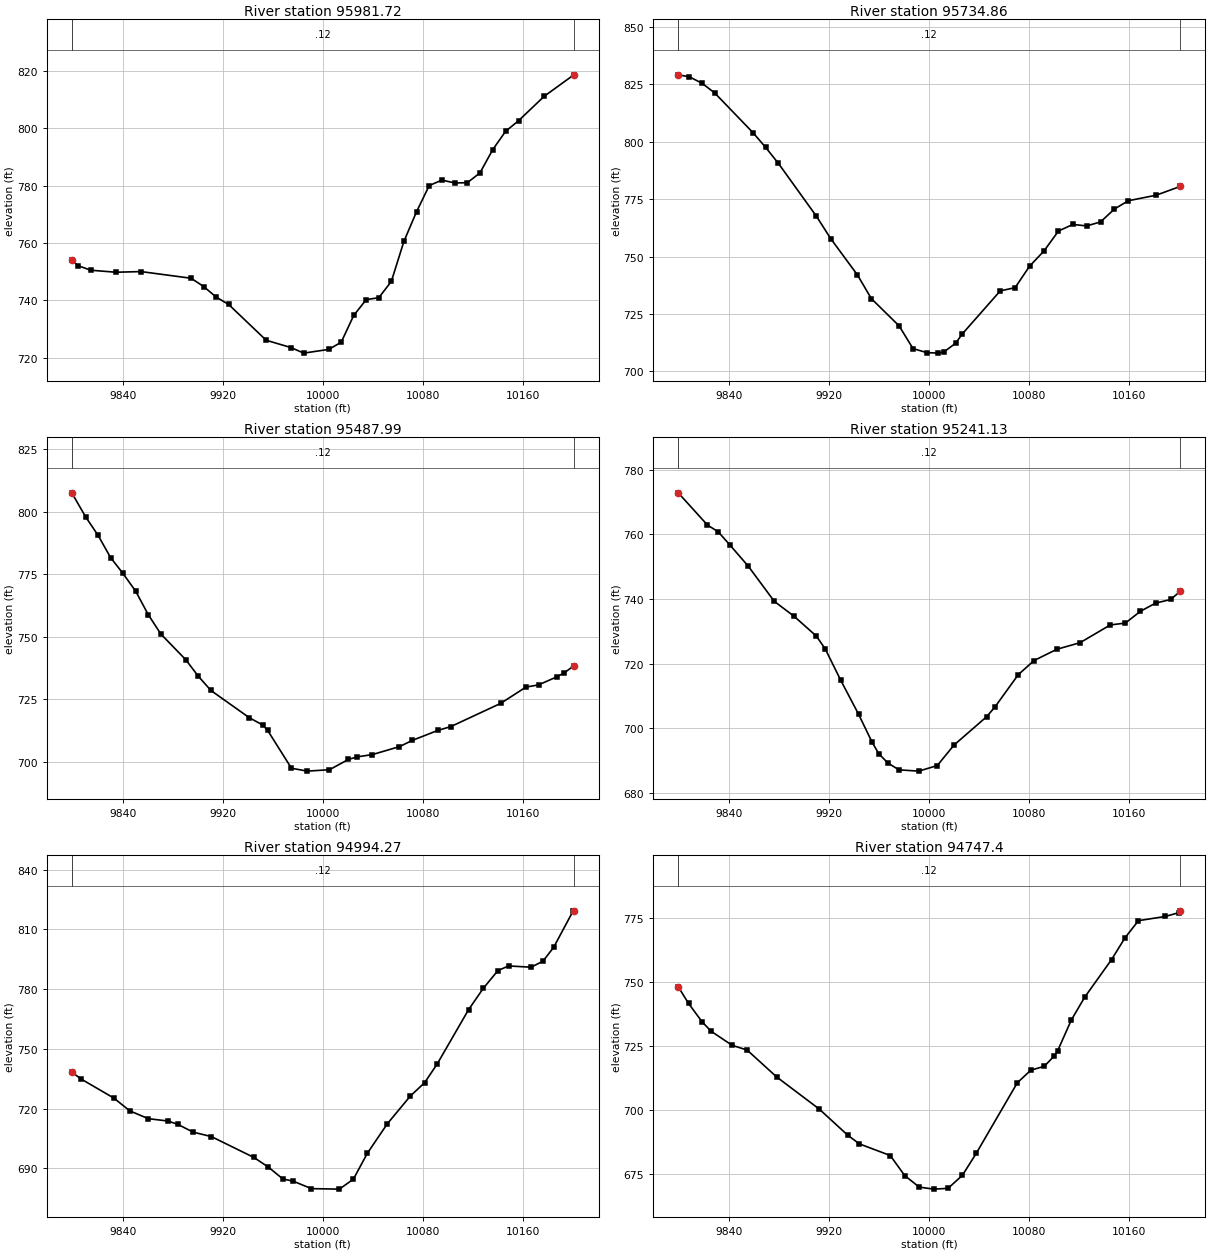
Type RM Length L Ch R = 1 ,95981.72,246.864100,246.864100,246.864100
XS GIS Cut Line= 6
450570.813024417781479.700435348 450578.89767594781592.688833196
450583.933315084781702.086296391450587.375717298781740.466112693
450598.374036704781807.399623867450616.419353421781877.917790038
#Sta/Elev= 30
9799.005753.93519804.318752.01949814.344750.47219834.395 749.7829854.446750.0059
9894.548747.67929904.574744.80089914.596741.12569924.606738.54119954.637726.0702
9974.658723.49449984.669721.578110004.69722.8734 10014.7725.371510024.72734.7141
10034.76740.2344 10044.8740.904110054.84746.575410064.92760.558810075.06770.9122
10085.19 780.00410095.33781.903510105.46780.917210115.59780.974710125.73  784.37
10136.01 792.51810146.33 798.91510156.65802.585810177.29811.146810200.95818.5996
#Mann= 3 , 0 , 0
9799.005    0.12       09799.005    0.12       010200.95    0.12       0
#XS Ineff= 2 , 0
       0                               0
Bank Sta=9799.005,10200.95
Exp/Cntr=0.3,0.1

Type RM Length L Ch R = 1 ,95734.86,246.864100,246.864100,246.864100
XS GIS Cut Line= 6
450280.985220192781526.371843014450297.729977736781609.583990199
450315.397704607781662.583609721450346.974537055781727.099615692
450400.960777411781814.798312559450438.674763751781892.394632539
#Sta/Elev= 30
9799.053829.19739807.855828.35289818.055825.54139828.255821.28989858.857804.0126
9869.057 797.5429879.258790.59069909.723 767.5139921.057757.84669942.524741.9612
9953.639731.6548 9975.87719.77469986.986709.86969998.101708.118610007.36707.9008
10011.67708.399710021.08712.202810026.44716.262610056.82 735.02710068.73736.4355
10080.38745.842510091.89752.458210103.41761.109610114.92763.980810126.03763.3461
10137.15765.096210148.27770.725810159.39774.326910181.63776.729310200.97780.5707
#Mann= 3 , 0 , 0
9799.053    0.12       09799.053    0.12       010200.97    0.12       0
#XS Ineff= 2 , 0
       0                               0
Bank Sta=9799.053,10200.97
Exp/Cntr=0.3,0.1

Type RM Length L Ch R = 1 ,95487.99,246.864100,246.864100,246.864100
XS GIS Cut Line= 6
450183.749319639781563.984145836 450182.64822742781697.981266624
 450167.44673815781732.185470252450125.434450164 781783.38427067
450109.524018131781830.594721875450117.993128176781942.519844777
#Sta/Elev= 30
9799.109807.49819810.173797.91189820.217790.45349830.261 781.5319839.875775.4272
9850.312768.1117 9860.32758.79089870.328751.08979890.345740.76669900.354734.1795
9910.452728.48959941.248717.56979951.878714.68979955.776712.56869974.898697.3996
9987.581696.242310005.31696.801310020.51700.935210027.73701.970110039.56702.8444
10061.34 706.04510071.67708.5445 10092.2712.556110102.25  714.0110142.34723.3357
 10162.5729.838610172.63730.720910187.37733.968910193.14735.528210200.85738.3263
#Mann= 3 , 0 , 0
9799.109    0.12       09799.109    0.12       010200.85    0.12       0
#XS Ineff= 2 , 0
       0                               0
Bank Sta=9799.109,10200.85
Exp/Cntr=0.3,0.1

Type RM Length L Ch R = 1 ,95241.13,246.864200,246.864200,246.864200
XS GIS Cut Line= 6
449821.978451055781668.431789129449861.439081494781727.293348995
449904.664085032781785.994629699449965.830168137781858.457839036
450001.640773696781904.713799992450060.485599129781991.401951241
#Sta/Elev= 30
9799.022772.81959822.407762.85979831.009760.77749840.365756.69579855.087750.1347
9875.893739.27239891.876734.60589909.623728.50449916.714724.54299929.132714.8339
9943.331704.39289954.222695.69829959.557692.1445 9966.92689.24479975.782687.1501
9991.547686.759810006.39688.482910019.73694.797410045.96703.605510052.66706.6511
10071.25716.5971 10083.9720.963810102.16724.4501 10120.7 726.47710144.87731.9617
10156.96732.543810169.04736.189610181.13738.709710193.22739.835410200.95742.3841
#Mann= 3 , 0 , 0
9799.022    0.12       09799.022    0.12       010200.95    0.12       0
#XS Ineff= 2 , 0
       0                               0
Bank Sta=9799.022,10200.95
Exp/Cntr=0.3,0.1

Type RM Length L Ch R = 1 ,94994.27,246.864100,246.864100,246.864100
XS GIS Cut Line= 6
449619.133856632781896.004736269449678.157907447781944.715961242
449730.664433589781981.672954212449761.860076783 782000.31652111
449853.653260202   782048.821209449955.608230891782113.977366104
#Sta/Elev= 30
9799.047738.35689806.652734.82799832.584725.36449845.549718.87959860.311714.9547
9876.069713.78979883.942712.09839896.171708.20989910.816705.96299944.835695.4881
9956.484690.62959968.134684.62659976.126683.62669990.891679.823610013.29679.5806
10024.48684.568810035.69697.611510051.63712.360110070.06726.305310081.55733.0375
10091.79742.638310116.74769.739410128.46780.382110140.19789.324810148.72791.6609
10166.76791.030410176.22794.0212 10184.8800.980110200.26819.095310200.99819.3382
#Mann= 3 , 0 , 0
9799.047    0.12       09799.047    0.12       010200.99    0.12       0
#XS Ineff= 2 , 0
       0                               0
Bank Sta=9799.047,10200.99
Exp/Cntr=0.3,0.1

Type RM Length L Ch R = 1 , 94747.4,246.864100,246.864100,246.864100
XS GIS Cut Line= 6
449489.027472657782120.447950493449549.716383445782160.609453042
449634.789389116782206.648332408449686.861402011782236.690163751
449727.044333761782254.866542336449846.108119034782302.401998983
#Sta/Elev= 30
9799.049748.21339807.297741.69379818.202734.47379825.418730.80499842.185725.3284
9854.176 723.4789877.831 712.9599911.942700.39769934.683690.2037 9944.08686.7866
9968.799682.23939980.388674.37929991.978669.901510003.56669.102310015.05 669.407
10026.54674.507110037.61683.083610070.53  710.7110081.34715.603410092.11717.1194
10100.11721.203510102.88 723.29210113.65735.143510124.41744.119410145.95758.8453
10156.72767.371710167.48774.052210189.02775.706610199.79777.179610200.98777.8998
#Mann= 3 , 0 , 0
9799.049    0.12       09799.049    0.12       010200.98    0.12       0
#XS Ineff= 2 , 0
       0                               0
Bank Sta=9799.049,10200.98
Exp/Cntr=0.3,0.1

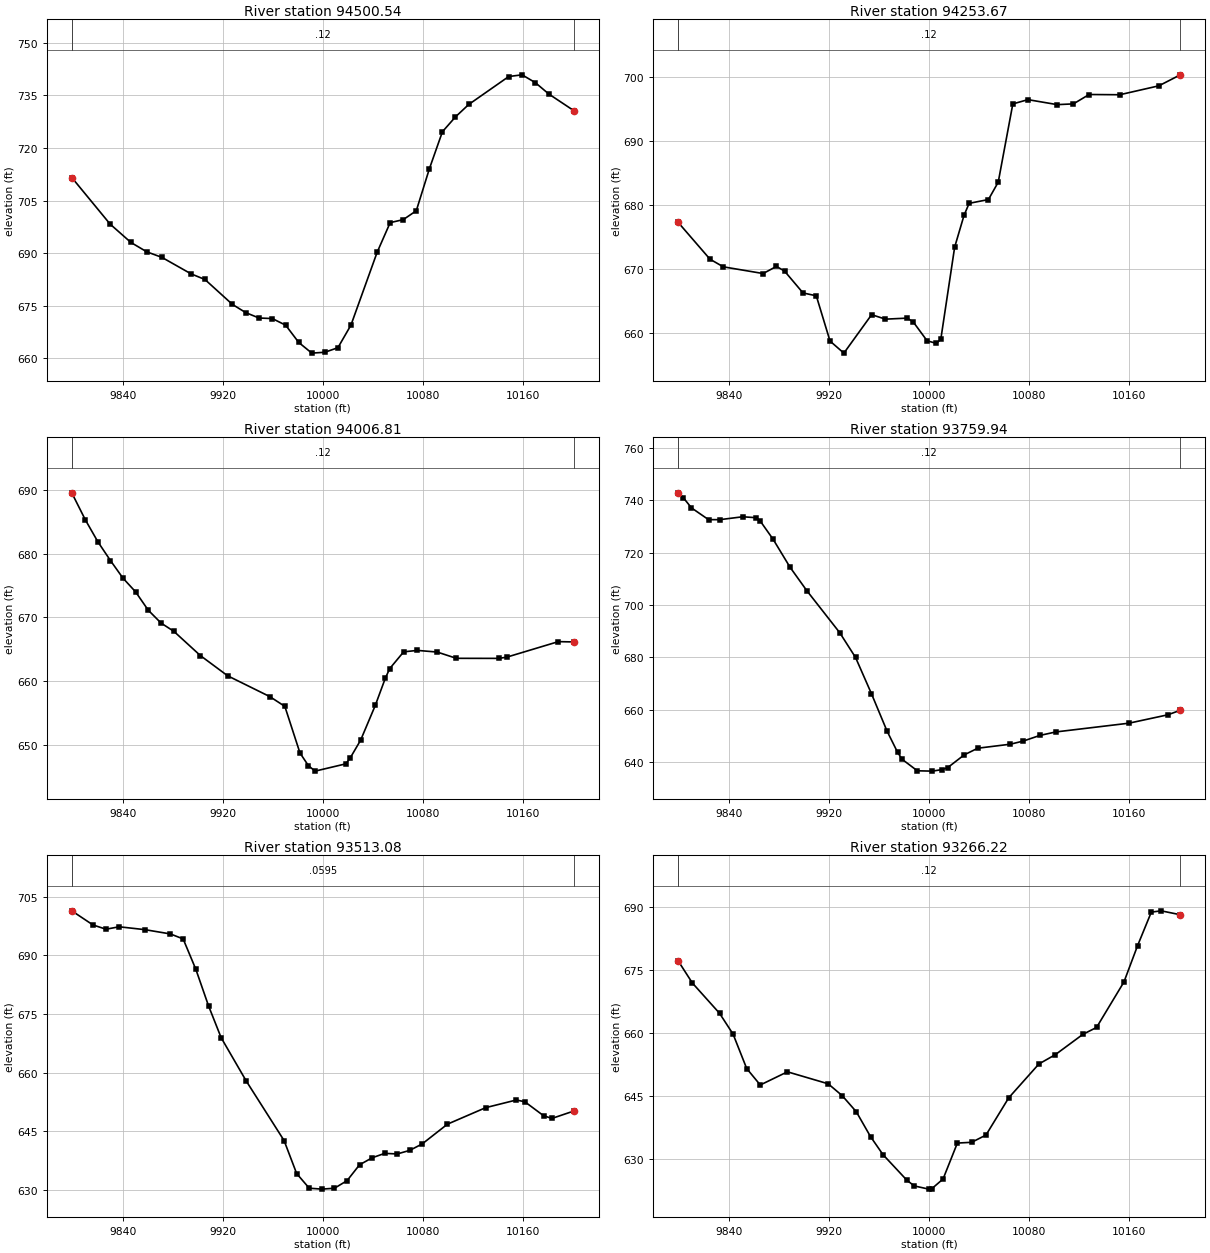
Type RM Length L Ch R = 1 ,94500.54,246.864100,246.864100,246.864100
XS GIS Cut Line= 6
449419.014530171782363.859035795449464.714731319782402.737140583
449517.945056636782432.206094068449565.958829385782450.192426988
 449697.51190845782490.274015841449783.836411534782522.457044157
#Sta/Elev= 30
9799.065711.59369829.766698.29649846.432693.05839859.138690.38359871.177688.8135
9894.554684.10379905.665682.49619927.583675.40739938.261673.0527 9948.94671.5085
9959.618671.34599970.297669.45599980.767664.52849991.214661.485610001.65661.7328
10012.11663.034810022.57669.501810043.48690.235110053.94698.720410064.39699.5709
10074.85702.107510085.31714.069910095.76724.652810106.22728.892910116.84732.4367
10148.85740.404910159.53740.8907 10170.2738.649110180.87735.433610200.97730.6668
#Mann= 3 , 0 , 0
9799.065    0.12       09799.065    0.12       010200.97    0.12       0
#XS Ineff= 2 , 0
       0                               0
Bank Sta=9799.065,10200.97
Exp/Cntr=0.3,0.1

Type RM Length L Ch R = 1 ,94253.67,246.864100,246.864100,246.864100
XS GIS Cut Line= 6
449395.994109787782481.113405096449434.560388081782587.446117828
449481.651728878782685.881486542449504.547383109782724.238520482
449530.459911902782762.420727506 449586.17295693782831.582087389
#Sta/Elev= 30
9799.066677.32259824.476671.58339835.113 670.3879867.025669.33729877.663670.4523
9884.137669.72749898.938666.30459909.575665.85689920.562658.77739931.662 656.892
9953.863662.90299964.963662.20459982.303662.36479987.164661.77349998.264658.8258
10005.74658.413110009.27659.091910020.33673.464910027.84678.441110031.92680.3172
10047.35680.904610055.21683.626110066.89695.860110078.98696.5303 10102.4695.7505
10115.37695.865410127.96697.332510152.49697.295910183.77698.690810200.96700.4102
#Mann= 3 , 0 , 0
9799.066    0.12       09799.066    0.12       010200.96    0.12       0
#XS Ineff= 2 , 0
       0                               0
Bank Sta=9799.066,10200.96
Exp/Cntr=0.3,0.1

Type RM Length L Ch R = 1 ,94006.81,246.864100,246.864100,246.864100
XS GIS Cut Line= 6
449312.192327975782434.079147313449307.973764126782495.055623055
449292.707046859782545.289652277449203.409631241782704.791030992
449199.589620628782748.795497153449214.506634925782806.734061684
#Sta/Elev= 30
9799.111689.54639810.033685.28479820.033681.84939830.034678.92369840.111676.1491
9850.199673.99999860.287671.12969870.577669.10179880.869667.79649901.991664.0057
9923.843660.8289  9957.6657.56049969.604656.0287  9981.7648.72059988.434646.7311
9993.796645.865310018.36 647.00710021.79 647.89310030.25650.723110041.99656.1868
10050.02660.456110053.54661.960910064.67664.588210075.64664.813810091.52664.5555
10106.88663.571110140.83663.560910147.12663.751110188.45  666.1910200.86666.1422
#Mann= 3 , 0 , 0
9799.111    0.12       09799.111    0.12       010200.86    0.12       0
#XS Ineff= 2 , 0
       0                               0
Bank Sta=9799.111,10200.86
Exp/Cntr=0.3,0.1

Type RM Length L Ch R = 1 ,93759.94,246.864200,246.864200,246.864200
XS GIS Cut Line= 6
448892.300296112  782487.2582517448932.532086606782530.438868119
448975.120153936782569.425536537449100.857720166782663.088242535
449127.806171161782697.566762661 449170.02259435782770.605797646
#Sta/Elev= 30
9799.045742.82079803.005741.02599809.626737.08079823.294732.58659832.344732.5742
9850.629733.67769861.409733.32779864.818731.95859874.966725.09919888.524714.4201
9902.081705.39029928.315689.41959940.981679.95149953.647666.19549966.207651.8293
9974.632643.73779978.319641.05739990.432636.691110002.51636.564910010.17637.1529
10014.61637.861210027.96642.770810038.79645.3113   10065646.853310075.28648.0507
10088.45650.186110101.25 651.52510159.81654.8682 10190.9658.063610200.93659.7976
#Mann= 3 , 0 , 0
9799.045    0.12       09799.045    0.12       010200.93    0.12       0
#XS Ineff= 2 , 0
       0                               0
Bank Sta=9799.045,10200.93
Exp/Cntr=0.3,0.1

Type RM Length L Ch R = 1 ,93513.08,246.864100,246.864100,246.864100
XS GIS Cut Line= 6
448778.789272347782817.744981108448822.831924767782831.315909136
448879.945036954782843.100797368449091.681728557782866.955412727
449128.714935149782876.529137307449171.161878162782894.392424398
#Sta/Elev= 30
9799.057701.41719816.019697.80489826.483696.70819836.947697.33449857.567696.6001
9877.988695.50439888.199694.2271 9898.41686.4068 9908.55677.07099918.622 668.941
9938.766657.82769968.981642.62699979.053634.17269989.124630.42899999.197630.1906
 10009.3630.421510019.37 632.351 10029.4636.420610039.43638.203710049.47639.3422
 10059.5639.195510069.53640.101710079.56641.764510099.73646.814710130.37651.0433
10154.86653.001810161.68652.5533 10176.7648.972610183.38648.285910200.91650.1832
#Mann= 3 , 0 , 0
9799.057  0.0595       09799.057  0.0595       010200.91  0.0595       0
#XS Ineff= 2 , 0
       0                               0
Bank Sta=9799.057,10200.91
Exp/Cntr=0.3,0.1

Type RM Length L Ch R = 1 ,93266.22,246.864100,246.864100,246.864100
XS GIS Cut Line= 6
448774.594129617783006.990064148448885.892778179783054.473223569
448912.449869664783068.284594736 448950.85415334783091.577701958
449012.439752751783125.853206746449136.191447334783181.277325658
#Sta/Elev= 30
9799.032677.12979810.345671.87499832.089664.65429842.961659.66069853.833651.4712
9864.705647.54789886.449650.68749919.065647.82949930.301644.99959941.573641.1613
9952.952635.23399962.919630.93969982.202624.78359988.039623.46029999.601622.6997
10002.09622.822810011.03625.113510022.48633.688210033.94 633.87110045.39635.5999
10063.62644.491410087.75652.557210101.04654.807510122.96659.625910133.92661.2776
10155.83672.120310166.79680.817510177.74688.785410185.61689.095710200.96688.1625
#Mann= 3 , 0 , 0
9799.032    0.12       09799.032    0.12       010200.96    0.12       0
#XS Ineff= 2 , 0
       0                               0
Bank Sta=9799.032,10200.96
Exp/Cntr=0.3,0.1

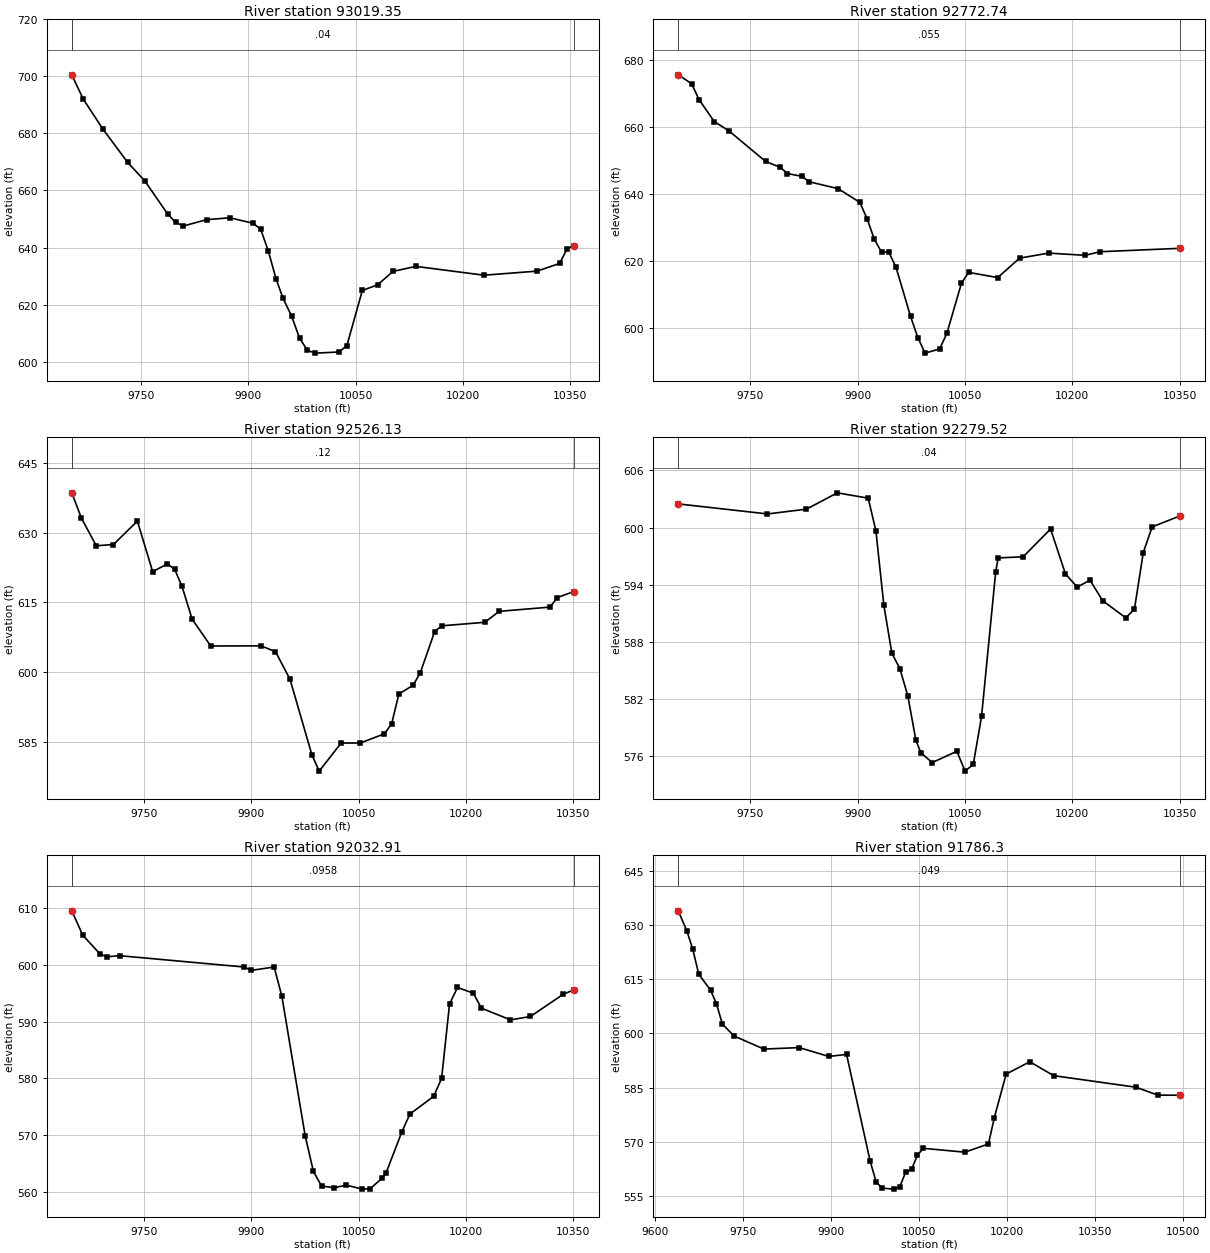
Type RM Length L Ch R = 1 ,93019.35,246.611300,246.611300,246.611300
XS GIS Cut Line= 6
448520.264016858783144.769944545448564.037288907783176.745888421
448605.937516993783199.847159961448789.063399489783277.150767974
448872.164174416783315.575150444449163.697573871783419.292987176
#Sta/Elev= 30
 9653.29700.5075 9669.29692.02759696.717681.54369731.511669.8173 9755.42663.3498
9787.341651.76239798.325 648.8749809.308647.57469841.838649.78859874.237650.4409
9906.637648.53839917.437646.44219928.237638.66959939.037628.92079948.531622.3441
9960.771615.92859971.797608.23649982.823604.01679993.848603.0444 10026.9603.4416
 10037.9605.673110059.52624.995910080.94626.965310102.35631.667210134.28633.4216
10229.57630.336910303.68631.754510335.44634.457610346.03639.683910355.24640.7113
#Mann= 3 , 0 , 0
 9653.29    0.04       0 9653.29    0.04       010355.24    0.04       0
#XS Ineff= 2 , 0
       0                               0
Bank Sta=9653.29,10355.24
Exp/Cntr=0.3,0.1

Type RM Length L Ch R = 1 ,92772.74,246.611300,246.611300,246.611300
XS GIS Cut Line= 6
448457.399590833783470.521810815448506.899098994783487.505003793
448555.293708985783499.162893136 448969.83115314783570.424171707
449053.302657587783587.886266547449144.246838135 783611.25590843
#Sta/Elev= 30
 9649.04675.51389667.648672.8973 9678.22668.11519699.364661.59859719.991658.8113
9771.195649.69939791.537647.96679801.708646.10349822.004645.27069832.123643.6473
9872.602641.60249902.961 637.5119913.081632.62769923.201626.51159933.321622.6739
 9943.44622.7002 9953.56618.15429973.842 603.5499984.013597.23619994.184592.6031
10014.51  593.8610024.67598.528310044.99613.447310055.15616.652910095.78 615.107
10126.26620.904810166.89622.401210217.95621.739510238.38622.808210350.98623.8334
#Mann= 3 , 0 , 0
 9649.04   0.055       0 9649.04   0.055       010350.98   0.055       0
#XS Ineff= 2 , 0
       0                               0
Bank Sta=9649.04,10350.98
Exp/Cntr=0.3,0.1

Type RM Length L Ch R = 1 ,92526.13,246.611400,246.611400,246.611400
XS GIS Cut Line= 6
448438.351258594783736.490283673448507.706635216  783783.1855904
 448588.99349079783804.251032398448667.991347774 783802.27624546
448913.610408717 783766.57108139449117.555177382783790.659384861
#Sta/Elev= 30
9649.088638.54689662.631633.0937 9683.32627.16919707.311627.43889740.822  632.48
9762.163621.60279782.872623.28959793.002622.08339803.132618.46049817.307611.4029
9843.333605.62959913.642605.65669933.874604.40989954.133598.4904 9984.76582.2259
9994.969578.734510025.61584.770710052.62 584.78510086.19586.761210096.26588.9079
10106.29595.288710126.33597.208810136.35599.894410156.36608.731710166.36609.9692
10226.47610.719210246.58613.078710317.63613.984110327.86616.045210350.94617.3274
#Mann= 3 , 0 , 0
9649.088    0.12       09649.088    0.12       010350.94    0.12       0
#XS Ineff= 2 , 0
       0                               0
Bank Sta=9649.088,10350.94
Exp/Cntr=0.3,0.1

Type RM Length L Ch R = 1 ,92279.52,246.611300,246.611300,246.611300
XS GIS Cut Line= 6
448520.474030733783849.458052502448604.598406859783907.045721102
448766.649291485783975.630503452448888.777251936784041.252100991
449009.517111546784115.359158552449126.865250856784197.757332025
#Sta/Elev= 30
9649.077602.48049773.807601.42629828.313601.92759871.476603.6449 9914.64603.0834
9925.431599.64769936.553591.80799947.741586.78059958.929  585.189970.117582.2731
9981.305577.6394 9988.33576.314110004.18575.293810038.61576.480410050.09574.3936
10061.56575.109110073.13580.148410092.85595.316710096.38596.803710131.26596.9198
10169.63599.843510190.38595.123710206.91593.733410224.69594.470110242.43 592.307
10274.75590.505610286.86591.416610299.23597.369310311.59600.063710350.99601.2325
#Mann= 3 , 0 , 0
9649.077    0.04       09649.077    0.04       010350.99    0.04       0
#XS Ineff= 2 , 0
       0                               0
Bank Sta=9649.077,10350.99
Exp/Cntr=0.3,0.1

Type RM Length L Ch R = 1 ,92032.91,246.611300,246.611300,246.611300
XS GIS Cut Line= 6
448475.882527205783822.520024522448544.909638966783926.120463773
 448611.61630487784108.987445774448644.712678551784167.505545908
448722.667554347 784330.38469132448788.023339818784447.974471993
#Sta/Elev= 30
9649.138 609.5099664.544605.20049689.232601.83389698.802601.42049715.859601.6094
9889.777 599.6149900.269599.02679932.037599.61079942.792594.46229975.463569.8201
9986.893563.60989998.322561.020210016.19560.749310032.95561.185410055.23  560.49
10066.31560.579910082.82562.400410088.48563.346310110.66570.622610121.74573.7084
   10155576.835810166.09579.990210177.17 593.07910188.26596.006310210.43 595.007
10221.68592.370210262.37590.299910290.33 590.90110336.09594.809210350.93595.6055
#Mann= 3 , 0 , 0
9649.138  0.0958       09649.138  0.0958       010350.93  0.0958       0
#XS Ineff= 2 , 0
       0                               0
Bank Sta=9649.138,10350.93
Exp/Cntr=0.3,0.1

Type RM Length L Ch R = 1 , 91786.3,567.349100,567.349100,567.349100
XS GIS Cut Line= 3
448342.032534271783770.305434331448414.949201018784388.360989884
448552.844222188784575.889285624
#Sta/Elev= 30
9639.581633.97159654.377628.37069664.447623.27159674.516616.42349694.655611.9924
9704.724608.22429714.794602.58189734.932599.28669785.279  595.699845.695596.0919
9896.042593.6398 9926.25594.20489966.527564.60119976.597558.91819986.666557.1764
 10006.8556.896210016.87557.504210026.94 561.62810037.01562.393210047.08566.3179
10057.15568.198810127.64567.131610167.91569.390810177.98576.719910198.12588.7655
 10238.4592.177310278.89588.321710419.11585.121110456.35582.936510494.69582.8976
#Mann= 3 , 0 , 0
9639.581   0.049       09639.581   0.049       010494.69   0.049       0
#XS Ineff= 2 , 0
       0                               0
Bank Sta=9639.581,10494.69
Exp/Cntr=0.3,0.1

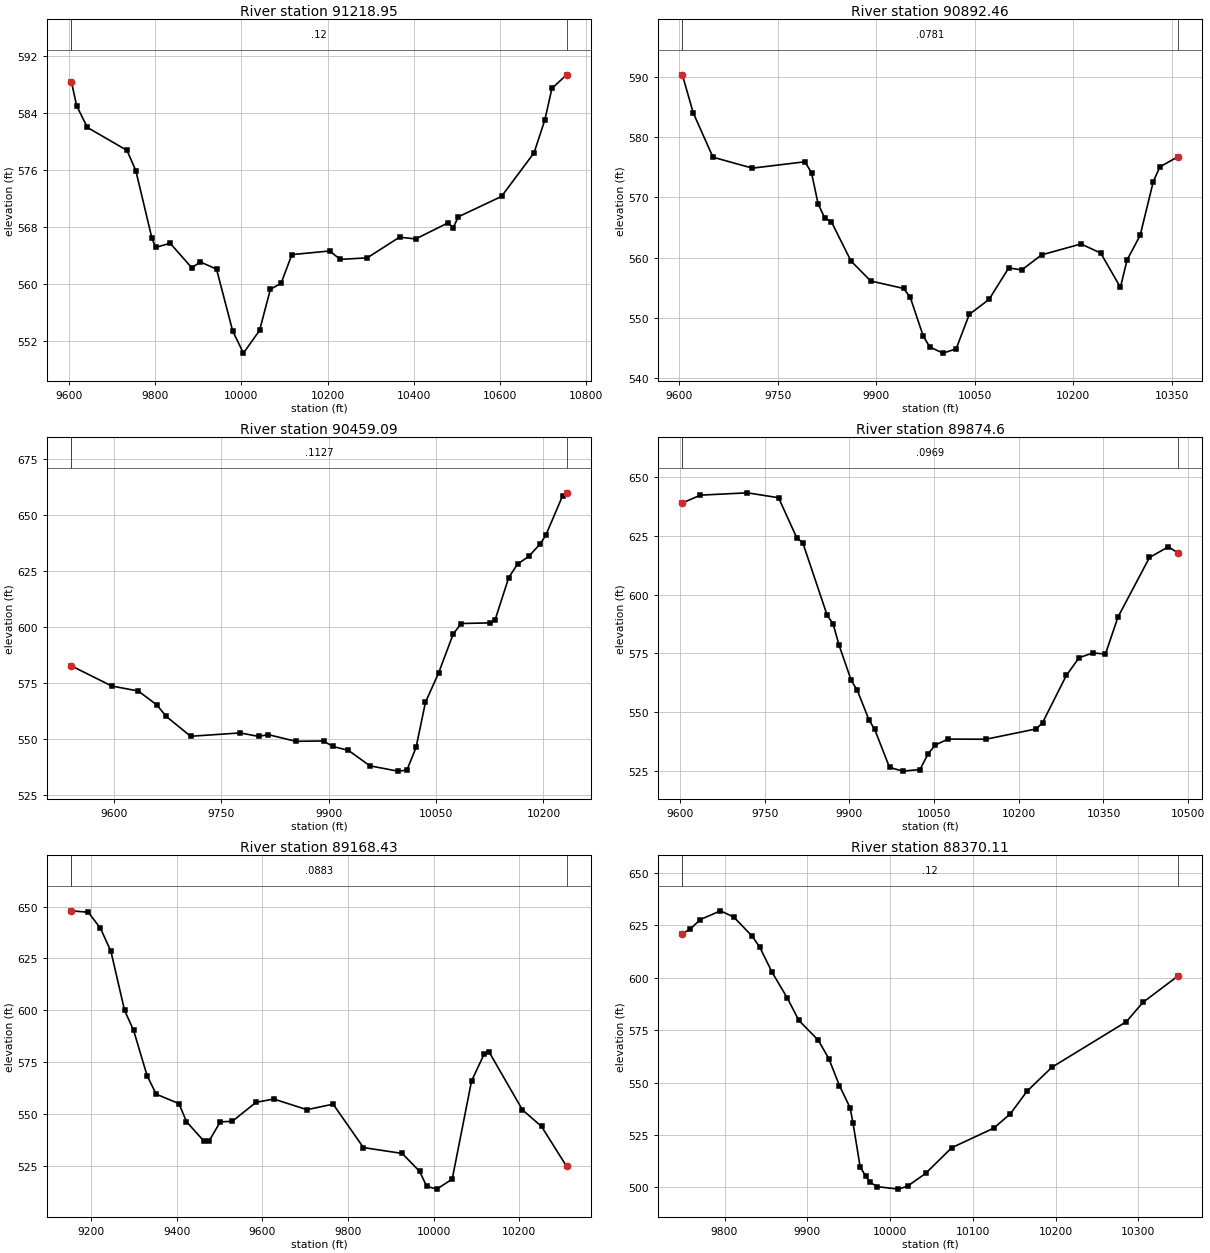
Type RM Length L Ch R = 1 ,91218.95,326.481800,326.481800,326.481800
XS GIS Cut Line= 2
447717.919453651784035.380026355448405.419453651784955.518915236
#Sta/Elev= 30
9606.001588.31759618.009584.98189642.975581.9333 9734.78578.71939755.323575.8961
9792.772566.39629801.608565.13639835.023565.70649885.144562.27889905.119563.0866
9942.568562.08649980.018553.418710004.98550.318610042.43553.5039 10067.4559.2509
10092.36560.107510117.33564.118610204.71564.625610229.68563.451710292.09563.6638
10366.99566.561910404.44566.312510479.34  568.5610491.82567.912310503.31569.4134
10603.55572.265510679.07578.380110704.03582.9801 10720.5587.406910754.61589.3019
#Mann= 3 , 0 , 0
9606.001    0.12       09606.001    0.12       010754.61    0.12       0
#XS Ineff= 2 , 0
       09881.825        10229.35       0
Bank Sta=9606.001,10754.61
Exp/Cntr=0.3,0.1

Type RM Length L Ch R = 1 ,90892.46,433.377400,433.377400,433.377400
XS GIS Cut Line= 2
447651.947231442784028.435581893447667.572231442784781.907804117
#Sta/Elev= 30
    9605590.28099621.568583.98489651.575576.64249711.588574.82969791.605575.8859
9801.607574.04179811.609568.91479821.611566.59129831.614 565.995 9861.62559.4577
9891.626556.14989941.637554.91029951.639553.49999971.644547.00849981.646545.2069
10001.65544.200410021.65544.904910041.66550.613610071.67553.086410101.67558.3036
10121.68557.980510151.68560.4659 10211.7562.2762 10241.7560.766210271.71555.0863
10281.71 559.60310301.71563.700410321.72 572.60910331.72575.044410358.63576.6838
#Mann= 3 , 0 , 0
    9605  0.0781       0    9605  0.0781       010358.63  0.0781       0
#XS Ineff= 2 , 0
       09867.276        10185.46       0
Bank Sta=9605,10358.63
Exp/Cntr=0.3,0.1

Type RM Length L Ch R = 1 ,90459.09,584.482600,584.482600,584.482600
XS GIS Cut Line= 2
447617.225009203784049.268915251447082.502786994 784488.50502634
#Sta/Elev= 30
9540.361582.77739596.654 573.8319633.829571.57679659.711565.39659672.653560.3162
9706.935551.40159776.182552.89289802.065551.32949815.006552.16369853.829549.1509
9892.653549.29029905.594546.85649927.498545.11299957.359538.22569996.182535.8506
10009.12536.243410022.03546.481510035.01566.488210053.53579.702110073.83596.9943
10085.04601.704710125.59601.982410132.31603.257510151.48 622.21410163.82628.2298
10179.57631.662810195.32637.181710203.24641.044710226.83658.766910232.36659.9982
#Mann= 3 , 0 , 0
9540.361  0.1127       09540.361  0.1127       010232.36  0.1127       0
#XS Ineff= 2 , 0
       09752.156                       0
Bank Sta=9540.361,10232.36
Exp/Cntr=0.3,0.1

Type RM Length L Ch R = 1 , 89874.6,706.174800,706.174800,706.174800
XS GIS Cut Line= 6
447565.986901343 783920.80462262447410.348080039783840.095152304
447255.309708387783784.340042979447229.681130409783796.323282033
447174.516675949783853.088359684446790.402092546784041.890443027
#Sta/Elev= 30
9604.327639.00229636.436642.33269719.412643.31489774.637641.23689806.943 624.167
9817.661622.00549860.532 591.341 9871.25587.53629881.967578.36849903.403563.4389
9914.121559.24919935.017546.55329944.857542.6584 9971.16526.45049994.826524.8653
10025.13525.5523 10039.8532.346610052.56536.026810074.93538.503310141.78538.4323
10230.92542.835310242.07545.448710284.21565.569110306.88573.149410331.21575.1604
10353.49574.705610375.78590.483710431.49615.796210464.92620.331410481.19617.8475
#Mann= 3 , 0 , 0
9604.327  0.0969       09604.327  0.0969       010481.19  0.0969       0
#XS Ineff= 2 , 0
       0                               0
Bank Sta=9604.327,10481.19
Exp/Cntr=0.3,0.1

Type RM Length L Ch R = 1 ,89168.43,798.318700,798.318700,798.318700
XS GIS Cut Line= 6
447462.204754651783837.174007833447208.298504591783749.283382818
447141.024199039783703.710466176447048.793296248783607.139285624
446992.822009414783566.254263222446550.384731442783155.605720818
#Sta/Elev= 30
9153.808647.92499193.179647.23799221.595 639.5099246.089628.37869277.836 600.003
    9299 590.3279330.747568.35479351.911559.5538 9405.02555.01699422.496546.3182
9462.715537.06569474.794 536.8439501.454 546.2199529.626546.48999584.869555.6381
9626.422557.22149703.908552.0871    9765554.75999835.775533.83249926.335530.9999
9966.816522.40289983.604515.1618 10007.3513.805710043.18518.652110088.26565.8893
10117.65578.838110128.74580.101410207.02552.0378 10251.7 544.02910310.38524.7589
#Mann= 3 , 0 , 0
9153.808  0.0883       09153.808  0.0883       010310.38  0.0883       0
#XS Ineff= 2 , 0
       0                               0
Bank Sta=9153.808,10310.38
Exp/Cntr=0.3,0.1

Type RM Length L Ch R = 1 ,88370.11,488.026300,488.026300,488.026300
XS GIS Cut Line= 6
447542.085049093783823.740409613447427.498294324 783724.86458376
447377.389086068 783657.32530202 447352.49867481783606.417646885
  447330.7173886783480.240675211447336.843064785783303.175165236
#Sta/Elev= 30
9749.068 621.0159758.132623.07469770.925627.7618 9795.15631.90069811.184  628.94
9833.239619.90419842.574614.60689857.521602.5598 9875.61590.50729889.882579.6141
9913.233570.2328 9926.05561.42979938.867 548.5619951.685538.03989955.193530.9153
9963.815509.94159970.673505.26159975.686 502.4539984.796500.372310010.21499.2078
10021.23500.653710043.01506.698210074.43518.935810125.34528.290610145.38535.1351
10165.42545.848910195.44557.2917 10285.5579.025110305.51 588.24210347.37600.6839
#Mann= 3 , 0 , 0
9749.068    0.12       09749.068    0.12       010347.37    0.12       0
#XS Ineff= 2 , 0
       0                               0
Bank Sta=9749.068,10347.37
Exp/Cntr=0.3,0.1