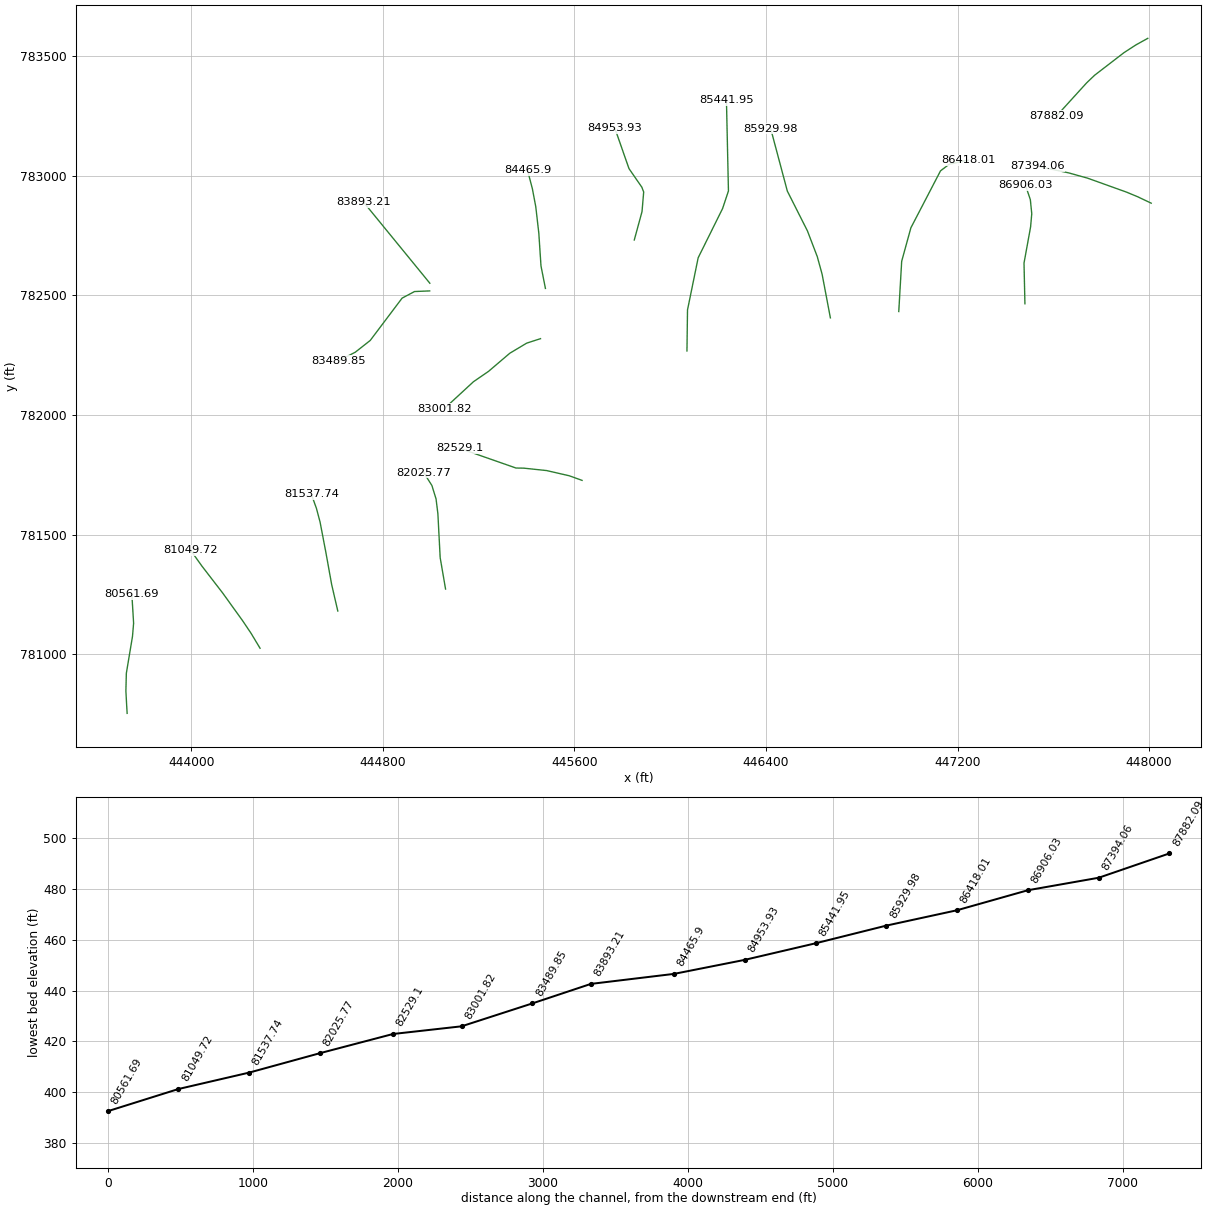
HEC-RAS study 2953_ras.prj: 2953

--- 2953_ras.g01 (geometry) --- (continued)

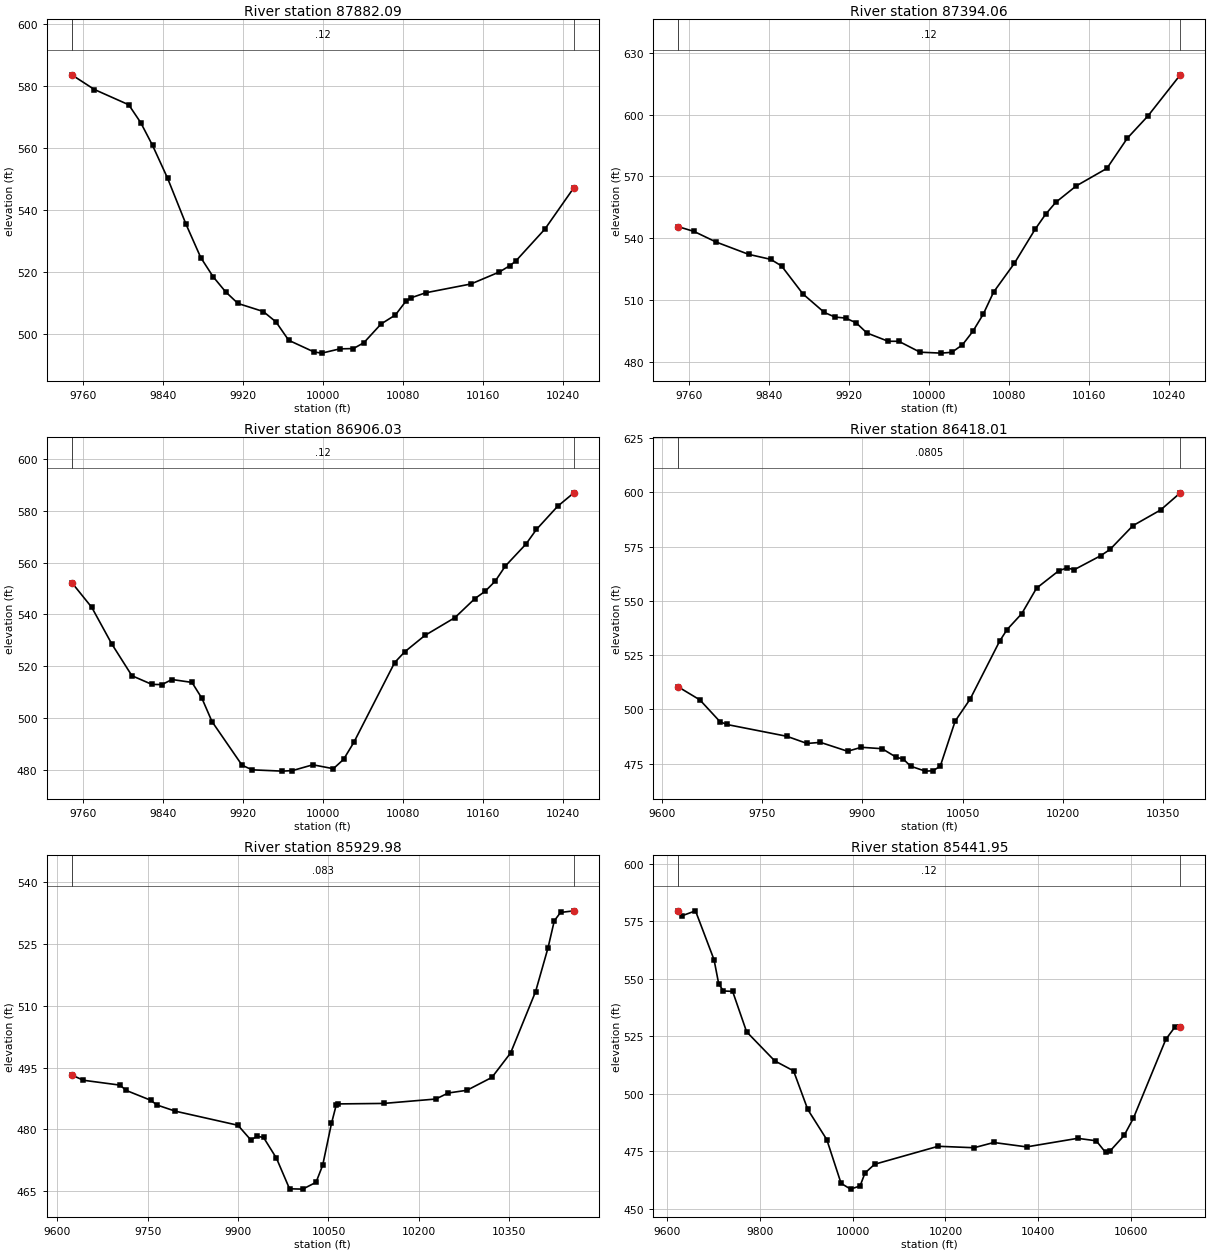
Type RM Length L Ch R = 1 ,87882.09,488.026400,488.026400,488.026400
XS GIS Cut Line= 6
447994.794194957783573.761391918447945.491290225783546.426666803
447895.376491365 783513.96605768 447772.71365711783419.590042677
447739.216370869783387.571671349447614.951980851783250.944422495
#Sta/Elev= 30
9749.028583.71899771.661578.97929805.987 574.0469817.901568.31159829.816560.9016
9844.814550.32239863.209535.47829877.969524.69529890.361518.49469902.753513.6597
9915.145509.87279940.454507.27059953.172503.9177 9965.89 497.9779991.326494.1857
    9999493.825710016.96495.199810030.58495.298310041.02 497.18510058.24503.2408
10072.61506.158510083.03510.5874 10087.7511.637210102.79513.314210148.08516.1621
10176.48  520.0310187.19522.118310193.09523.640110221.99533.878910250.96547.2477
#Mann= 3 , 0 , 0
9749.028    0.12       09749.028    0.12       010250.96    0.12       0
#XS Ineff= 2 , 0
       0                               0
Bank Sta=9749.028,10250.96
Exp/Cntr=0.3,0.1

Type RM Length L Ch R = 1 ,87394.06,488.026300,488.026300,488.026300
XS GIS Cut Line= 6
448009.141862168782885.168973344 447953.39490068782911.675764183
447905.495229198782931.541795409447743.711041445782989.594399934
447664.618636242783011.664746657447533.257935066 783039.92089212
#Sta/Elev= 30
9749.019545.61099764.678543.33469786.823538.18069819.424532.19259841.487529.7644
9852.313526.56299873.768512.94419895.046504.01419905.685 501.7699916.324501.2795
9926.963 498.9519937.602494.0592 9958.88490.02389969.519490.01419990.797484.7239
   10012484.270110022.56484.677710033.13488.290210043.54 494.81310053.92503.1373
 10064.3513.875310085.06527.831910105.83544.375610116.21551.579210126.44557.4199
 10146.9565.383610177.59573.905510198.05588.5733 10218.5599.265510250.97619.2884
#Mann= 3 , 0 , 0
9749.019    0.12       09749.019    0.12       010250.97    0.12       0
#XS Ineff= 2 , 0
       0                               0
Bank Sta=9749.019,10250.97
Exp/Cntr=0.3,0.1

Type RM Length L Ch R = 1 ,86906.03,488.026400,488.026400,488.026400
XS GIS Cut Line= 6
447481.577437452782465.033281294447477.808367938782634.982705751
447505.272140349782785.941177911447510.144605683782841.071744241
447504.262267921782899.692473722447483.957402871782960.035122499
#Sta/Elev= 30
9749.051552.33489769.057 542.7279789.096528.54459809.135516.29369829.174512.9308
9839.188512.85879849.188 514.8189869.188513.70139879.189507.51019889.199 498.558
9919.232481.6678 9929.31479.87229959.543479.37239969.621479.58179990.037481.8247
10010.49480.313710020.71483.907410030.93490.463310071.81521.398610081.87525.5447
10101.95531.855910132.05538.776710152.07546.165610162.15548.933310172.26552.8697
10182.38558.709210203.07567.242610213.48572.888310234.62581.824910250.88587.0572
#Mann= 3 , 0 , 0
9749.051    0.12       09749.051    0.12       010250.88    0.12       0
#XS Ineff= 2 , 0
       0                               0
Bank Sta=9749.051,10250.88
Exp/Cntr=0.3,0.1

Type RM Length L Ch R = 1 ,86418.01,488.026300,488.026300,488.026300
XS GIS Cut Line= 6
446954.629056271782432.552525744446966.825046182782642.564045034
447005.279860299782782.401410067447129.049699808783020.286702966
447165.490019725783047.909687374447244.336207282783064.919497975
#Sta/Elev= 30
9624.056510.35499656.512 504.347 9686.52494.34149696.523493.04069786.687487.5834
9816.897484.27749837.069484.77419877.701 480.6819898.248482.51019929.415 481.858
9950.433477.93489961.257477.03439972.082473.79049994.082 471.52310005.23471.6812
10016.42473.7371 10038.8494.592310061.17504.703310105.38531.428410116.43536.7424
10138.54544.120710160.65555.852410194.17563.937710205.83 565.12610217.48564.4233
10256.96570.854210270.63573.688210304.96584.654910346.42591.892910375.97599.8021
#Mann= 3 , 0 , 0
9624.056  0.0805       09624.056  0.0805       010375.97  0.0805       0
#XS Ineff= 2 , 0
       0                               0
Bank Sta=9624.056,10375.97
Exp/Cntr=0.3,0.1

Type RM Length L Ch R = 1 ,85929.98,488.026400,488.026400,488.026400
XS GIS Cut Line= 6
446668.992632329782406.086488456446634.451951534782588.278387055
446614.131994575782662.258314222446573.092327446782769.378772482
 446489.18370381782935.573156387446419.670032352783196.331993952
#Sta/Elev= 30
9624.049 493.1899643.231491.92279704.083490.73849714.225489.46039755.083487.0603
  9765.3 485.9189795.954484.41029899.778480.99139921.026477.43859931.649478.3183
9942.273478.02249963.635472.99639985.367465.563510007.21465.483710029.32467.1385
10040.37471.295910054.94481.438810062.63485.804210066.03486.174210141.49486.2932
10228.01487.361710248.71488.826910279.75489.487310321.15492.6153 10352.2498.5603
 10393.6513.451610414.29524.110410424.64530.645610434.99532.665110457.07533.0621
#Mann= 3 , 0 , 0
9624.049   0.083       09624.049   0.083       010457.07   0.083       0
#XS Ineff= 2 , 0
       0                10096.01       0
Bank Sta=9624.049,10457.07
Exp/Cntr=0.3,0.1

Type RM Length L Ch R = 1 ,85441.95,488.026300,488.026300,488.026300
XS GIS Cut Line= 6
446069.867002904782267.926071644446072.189927965782439.397286177
446116.697976738782657.092027724446218.755850226782862.958449036
446243.176558286782936.275717244446234.774199039783316.123660624
#Sta/Elev= 30
9624.044579.32419631.137 577.2959661.216579.5267 9701.25558.24439711.258547.7804
9721.266544.69019741.284544.4948 9771.38526.93289832.002514.29869872.563509.9579
9903.218493.15689944.207480.05899974.948461.06939995.442458.539610016.03459.9378
10026.43 465.52910047.27469.353410184.14477.165310261.58476.534210304.01478.8104
10374.84476.900910484.86480.619310524.87479.553910544.88474.502710554.88475.1582
10584.89481.854610604.89489.351310674.91523.686710694.91529.131410706.04529.1304
#Mann= 3 , 0 , 0
9624.044    0.12       09624.044    0.12       010706.04    0.12       0
#XS Ineff= 2 , 0
       0                10318.48       0
Bank Sta=9624.044,10706.04
Exp/Cntr=0.3,0.1

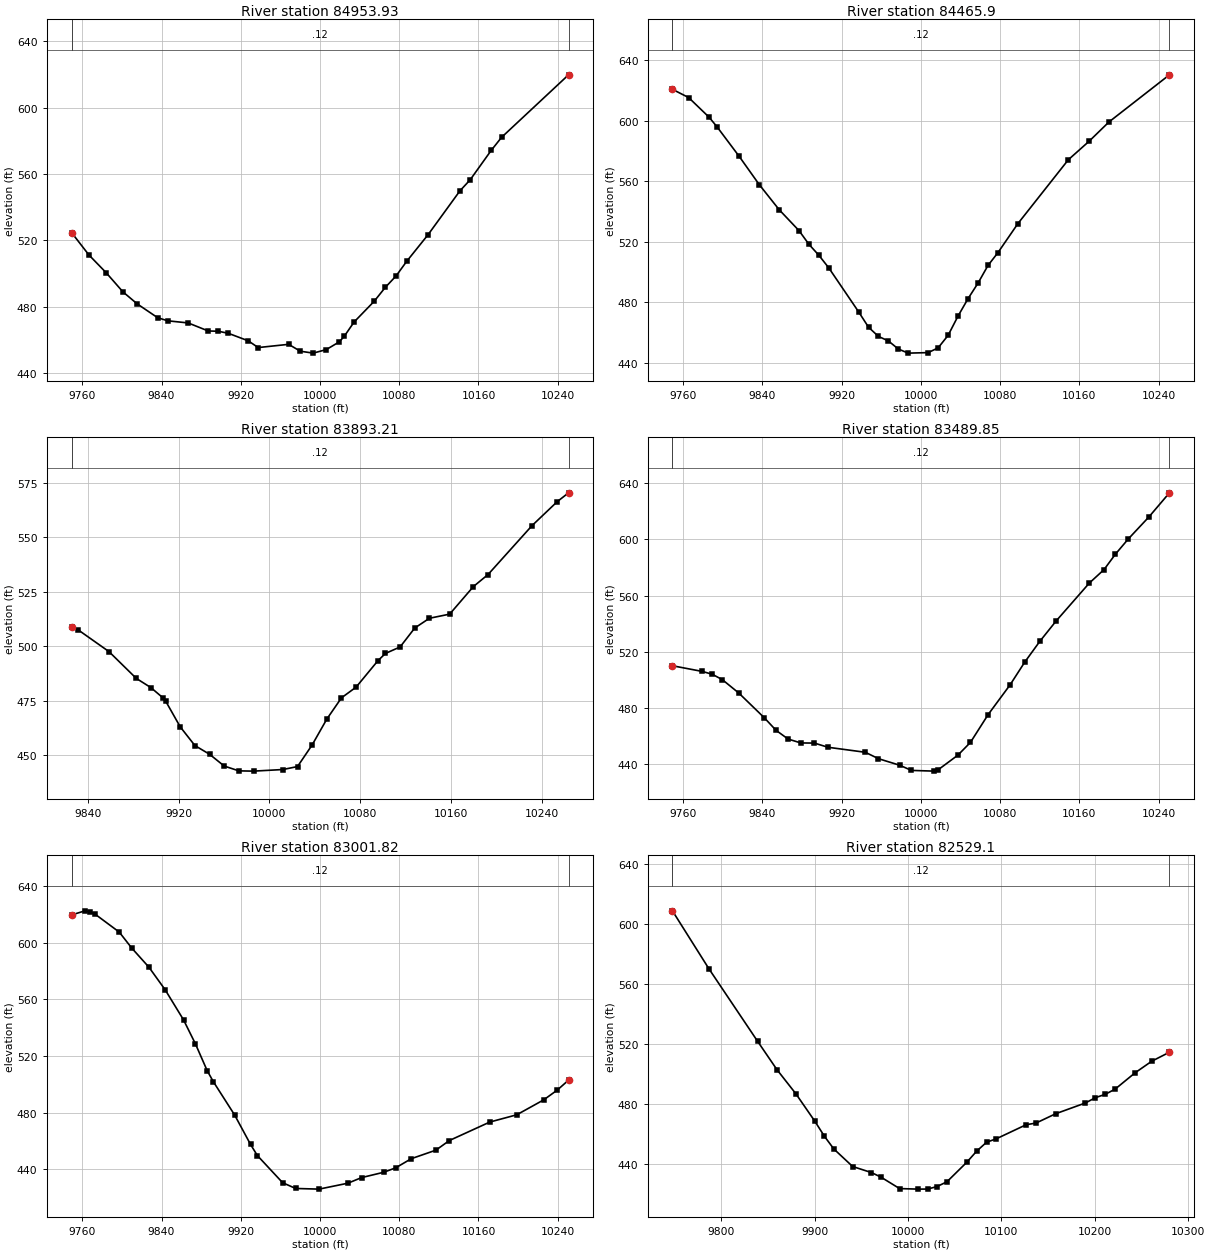
Type RM Length L Ch R = 1 ,84953.93,488.026300,488.026300,488.026300
XS GIS Cut Line= 6
445849.860493854782731.491167157445882.164504948 782849.89622986
445889.114607341782931.850878263 445881.38357768  782951.9921545
445827.688732541783029.665429477445768.360424392783199.310151329
#Sta/Elev= 30
 9749.15524.72259766.771511.15329784.182500.46579801.056488.94819815.502481.6986
9836.064 473.3989846.345471.51299866.907470.23319887.215465.38389897.327465.2297
 9907.44463.99169927.592459.45439937.605455.38949968.365457.34449980.116453.1991
 9993.18452.0413 10006.4 454.18610019.43458.807810024.56462.240510034.46470.8154
10054.73483.290710065.91491.638610076.86498.5896 10087.6507.404510109.09523.3805
10141.24549.793210151.76556.583310172.79574.1469 10183.3582.054610250.92619.7339
#Mann= 3 , 0 , 0
 9749.15    0.12       0 9749.15    0.12       010250.92    0.12       0
#XS Ineff= 2 , 0
       0                               0
Bank Sta=9749.15,10250.92
Exp/Cntr=0.3,0.1

Type RM Length L Ch R = 1 , 84465.9,572.692600,572.692600,572.692600
XS GIS Cut Line= 6
445478.659527964782529.117724038445460.127742036782623.248963687
 445451.08858149782759.643647682445438.386467067782870.161698248
445424.160791088782945.421409329445403.550313585 783024.07553576
#Sta/Elev= 30
9749.058620.86149765.442615.40819786.075602.43819794.192596.00349816.564576.4737
9836.781557.85629856.896 541.274 9876.94527.44729886.962518.39299896.984511.1692
9907.006502.82619937.072473.83999947.094463.66159957.116457.57089967.138454.6058
 9977.16449.25129987.198446.533610007.32446.873310017.38450.010210027.45458.2847
10037.52471.066410047.59482.538110057.66492.797310067.73504.451610077.79512.9532
10097.98532.165310148.87574.329810169.65586.427410189.89599.283410250.96630.4372
#Mann= 3 , 0 , 0
9749.058    0.12       09749.058    0.12       010250.96    0.12       0
#XS Ineff= 2 , 0
       0                               0
Bank Sta=9749.058,10250.96
Exp/Cntr=0.3,0.1

Type RM Length L Ch R = 1 ,83893.21,403.360100,403.360100,403.360100
XS GIS Cut Line= 2
444995.868964285782550.809247002444718.715171248782889.908382818
#Sta/Elev= 30
 9825.59508.80479831.003507.66539858.567497.52719882.663485.21289895.579480.9593
9905.972 476.3639908.494474.82199921.409462.92839934.324454.34679947.239450.3565
9960.154444.9375 9973.07442.72889985.985442.607810011.82443.343310024.73 444.703
10037.65454.669110050.56466.520710063.48 476.28810076.39481.214510095.59493.3424
10102.22496.676910115.14499.659910128.05508.359810140.97512.8335 10158.8 514.731
10179.71527.393310192.63 532.93210231.37555.392910253.61566.418610263.54570.4588
#Mann= 3 , 0 , 0
 9825.59    0.12       0 9825.59    0.12       010263.54    0.12       0
#XS Ineff= 2 , 0
       0                               0
Bank Sta=9825.59,10263.54
Exp/Cntr=0.3,0.1

Type RM Length L Ch R = 1 ,83489.85,488.026300,488.026300,488.026300
XS GIS Cut Line= 6
444995.204846733782518.761810979 444931.82578949782516.066596442
444880.024381128 782488.58882573444746.815149331782311.767454183
444684.610811747782262.843029284444616.115913513782227.512954566
#Sta/Elev= 30
9749.076509.99649779.341505.93389789.351503.91119799.446500.1147  9816.1490.5615
9841.887472.92729853.722464.00789865.835457.80839878.742 455.0279892.435454.9306
9906.076451.95469943.838448.37869957.131443.81199978.914439.07259990.361435.4657
10013.59 434.95610017.25435.842610037.36446.362310049.99455.409810067.91475.2751
10090.09496.468510104.81512.577610120.01527.344410136.51541.884610170.03 568.877
10184.88578.471710196.45589.521210209.48600.374910230.08615.882510250.91633.1326
#Mann= 3 , 0 , 0
9749.076    0.12       09749.076    0.12       010250.91    0.12       0
#XS Ineff= 2 , 0
       0                               0
Bank Sta=9749.076,10250.91
Exp/Cntr=0.3,0.1

Type RM Length L Ch R = 1 ,83001.82,472.726200,472.726200,472.726200
XS GIS Cut Line= 6
445458.191011387782319.284987541445400.459886416782300.604791187
445329.855133057782258.388212964445240.519695529782182.247274482
445178.060318794782139.397292859445056.596060197  782027.2770787
#Sta/Elev= 30
9749.114 619.4339762.667622.35659767.779 621.6169773.046619.9367 9797.29607.3596
9809.898596.10349827.305582.54639843.676566.62889862.212545.41479874.164528.5648
9886.116509.51029892.265501.82719913.806478.26579929.896457.46129936.757449.6485
9962.287430.47499975.441426.4257    9999425.960910028.19 430.14710041.95434.0939
10064.29437.851210076.39440.9804 10092.1447.4249   10117453.457410130.61460.2585
10171.43473.297710198.65478.416810225.87488.959810239.48 495.81910250.92502.8634
#Mann= 3 , 0 , 0
9749.114    0.12       09749.114    0.12       010250.92    0.12       0
#XS Ineff= 2 , 0
       0                               0
Bank Sta=9749.114,10250.92
Exp/Cntr=0.3,0.1

Type RM Length L Ch R = 1 , 82529.1,503.326500,503.326500,503.326500
XS GIS Cut Line= 6
445631.745155931781727.290386826445578.185508102781746.573213577
445483.526844114781768.319241747445388.235291302781778.385322228
445355.813640952781778.873679474445120.190865695781861.262549505
#Sta/Elev= 30
 9747.89608.84769786.944570.15549839.211521.56479859.764  502.779880.135486.5547
9900.506468.15769910.594458.24979920.665449.78029940.806438.05429960.945434.0021
9970.981431.01989991.053423.312710011.09422.948110021.09 422.99410031.14424.6721
10041.73427.851510062.92440.860310073.51448.287510084.11454.2544 10094.7456.6067
10126.48465.955510137.08467.084410158.26473.337910190.04480.523310200.64484.0454
10211.23486.286710221.83 489.77710243.01500.594410260.91508.368110279.89514.3919
#Mann= 3 , 0 , 0
 9747.89    0.12       0 9747.89    0.12       010279.89    0.12       0
#XS Ineff= 2 , 0
       0                               0
Bank Sta=9747.89,10279.89
Exp/Cntr=0.3,0.1

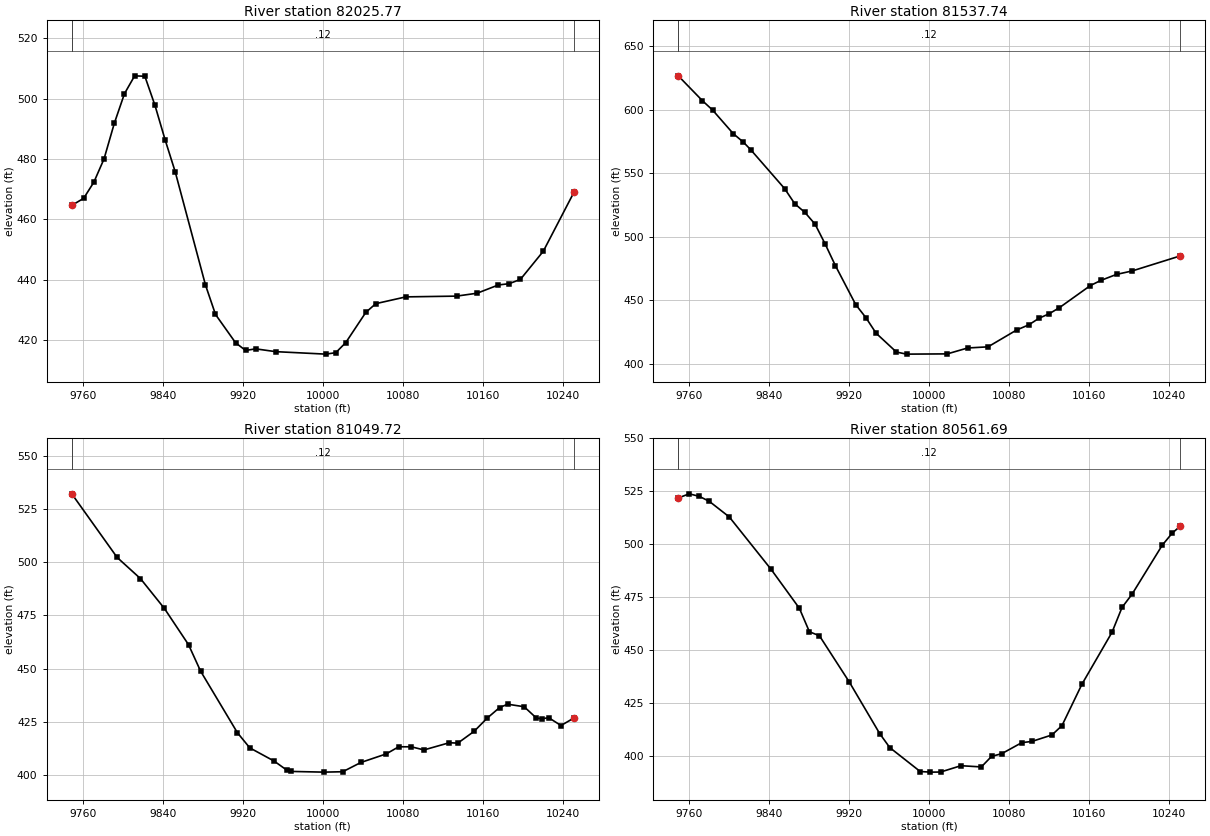
Type RM Length L Ch R = 1 ,82025.77,488.026400,488.026400,488.026400
XS GIS Cut Line= 6
445061.531690383781273.326732009445039.021107471781404.661660264
445029.428201138781588.310217737445021.836917285781649.720465019
445004.450204135781706.013891991444970.380394515781759.660317817
#Sta/Elev= 30
9749.028464.63219760.926466.9859 9771.12472.32419781.313480.05119791.506491.7542
9801.699501.59999811.893507.51019822.086507.36369832.191497.74329842.287486.3833
9852.383475.8064 9882.67438.30879892.701428.54779912.764419.18229922.795416.6389
9932.826 417.1679952.871416.2401 10002.9415.420410012.91415.892710022.92419.2363
10042.94429.221810052.94 432.12310083.02434.365210133.61434.6148 10154.2435.5729
10175.46438.3062 10186.1438.723510197.45440.136410220.32449.438910250.91468.9107
#Mann= 3 , 0 , 0
9749.028    0.12       09749.028    0.12       010250.91    0.12       0
#XS Ineff= 2 , 0
       0                               0
Bank Sta=9749.028,10250.91
Exp/Cntr=0.3,0.1

Type RM Length L Ch R = 1 ,81537.74,488.026300,488.026300,488.026300
XS GIS Cut Line= 6
444611.398831567781181.463461772444585.874204994781291.625455772
444561.581384633781426.350761269444537.333460907781553.232870319
444522.210623874781610.278410397 444500.57410966781670.251231128
#Sta/Elev= 30
9749.022626.45749773.182606.92759783.447599.49389803.976581.06949814.241574.2703
9821.673568.22849855.301537.91379865.531525.93049875.692519.10989885.854509.8652
9896.015494.15119906.176477.25879926.499446.6462 9936.66436.42169946.821424.2387
9967.144  409.439977.305407.799310017.99407.989310038.35412.629710058.71413.5175
10087.32426.751610099.43430.777710109.62435.9657 10119.8439.492910130.01444.2617
10161.04461.676410171.39465.678110187.19470.447910202.84473.157210250.95484.9841
#Mann= 3 , 0 , 0
9749.022    0.12       09749.022    0.12       010250.95    0.12       0
#XS Ineff= 2 , 0
       0                               0
Bank Sta=9749.022,10250.95
Exp/Cntr=0.3,0.1

Type RM Length L Ch R = 1 ,81049.72,488.026300,488.026300,488.026300
XS GIS Cut Line= 6
444286.591693658781026.142171688444249.125916773 781088.47716681
444213.645456794781141.276056352444129.931420737781257.600995656
444043.466098945781369.742168316443996.611581934781435.450677946
#Sta/Elev= 30
 9749.02 532.0939794.357502.22329817.691492.26559841.655478.22329865.751461.2323
9877.799448.81019914.638 419.8549926.979412.75599951.309406.54769964.002 402.292
9968.374401.677510000.99401.350810019.91401.532410038.02405.876810063.28409.8868
 10075.9413.260310088.53413.248910101.16411.778410126.41415.154310135.02414.9825
10151.39420.5589 10164.3426.700410176.74431.684710184.87433.2619 10201.3432.0696
10213.59426.738210219.31426.428510225.87426.924410238.15423.238210250.99426.7651
#Mann= 3 , 0 , 0
 9749.02    0.12       0 9749.02    0.12       010250.99    0.12       0
#XS Ineff= 2 , 0
       0                               0
Bank Sta=9749.02,10250.99
Exp/Cntr=0.3,0.1

Type RM Length L Ch R = 1 ,80561.69,488.026400,488.026400,488.026400
XS GIS Cut Line= 6
443731.349822261780754.040870074443726.207720331780846.817423178
443728.125178027780921.621894897443753.795676044781075.337600057
443758.456861239781130.509029114443751.040998449781252.964774884
#Sta/Elev= 30
9749.065521.85699760.041523.80429770.056522.62499780.071520.27899800.102512.8984
9841.984488.14819870.176 469.8339880.179458.78689890.182 456.9139920.215434.9889
9950.432410.79789960.505404.19699990.935392.915410001.07392.628810011.26392.6672
10031.65395.656710052.04395.079210062.23 400.04510072.43401.3272 10092.5406.5339
10102.54407.092810122.61410.150310132.63414.545710152.63434.105910182.64458.5371
10192.67 470.25910202.72476.531510232.86 499.58310242.91505.328410250.92 508.576
#Mann= 3 , 0 , 0
9749.065    0.12       09749.065    0.12       010250.92    0.12       0
#XS Ineff= 2 , 0
       0                               0
Bank Sta=9749.065,10250.92
Exp/Cntr=0.3,0.1