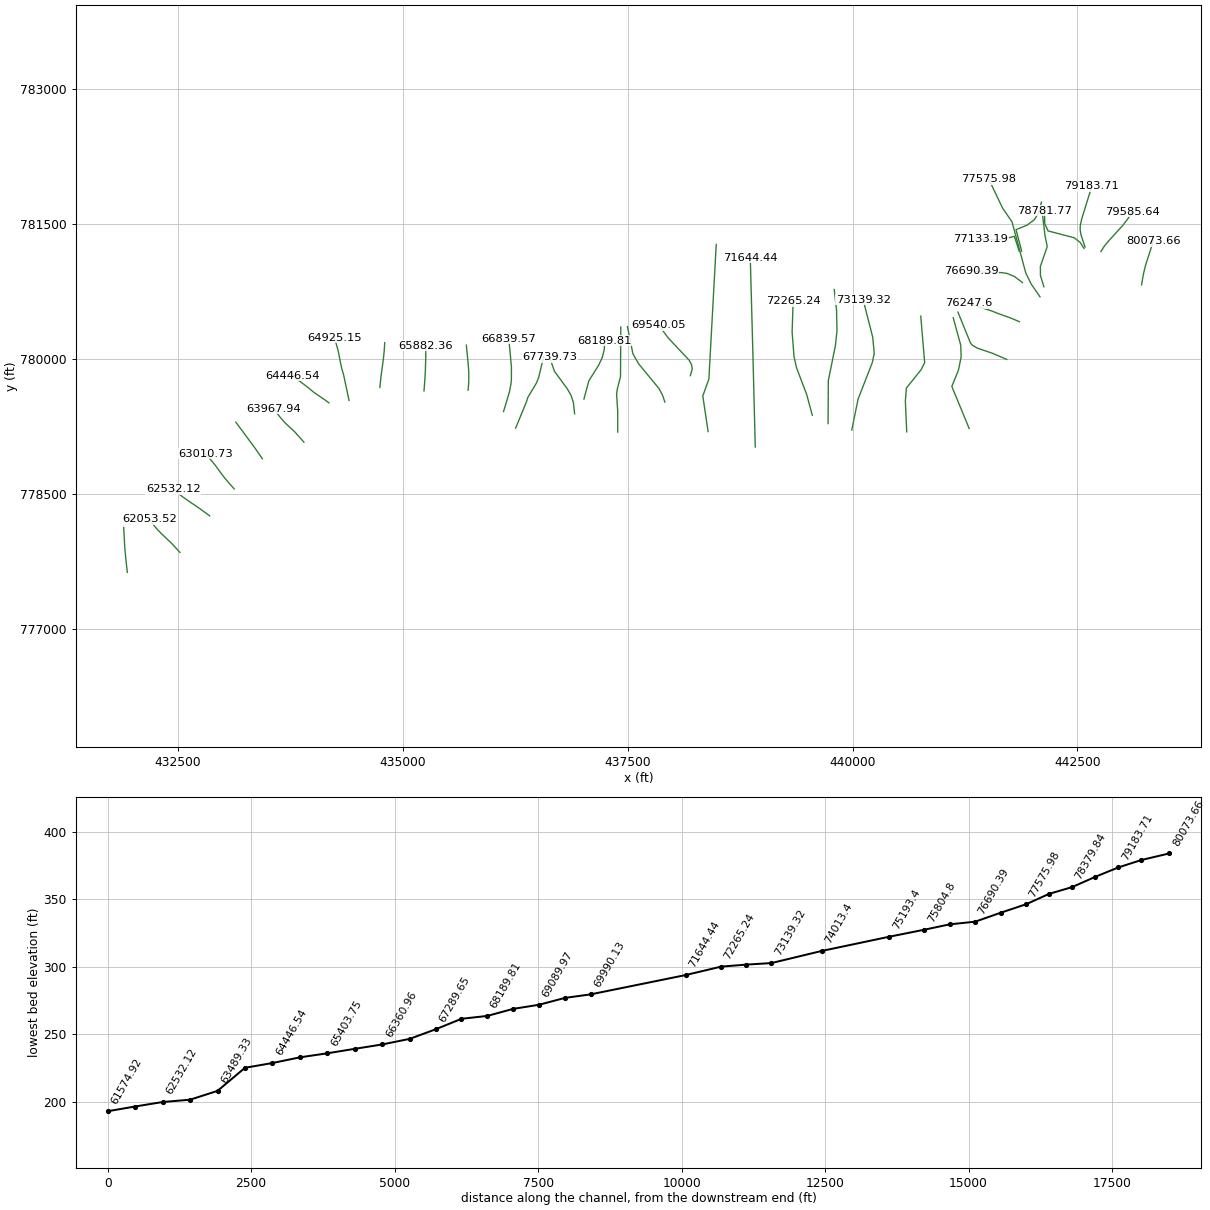
HEC-RAS study 2953_ras.prj: 2953

--- 2953_ras.g01 (geometry) --- (continued)

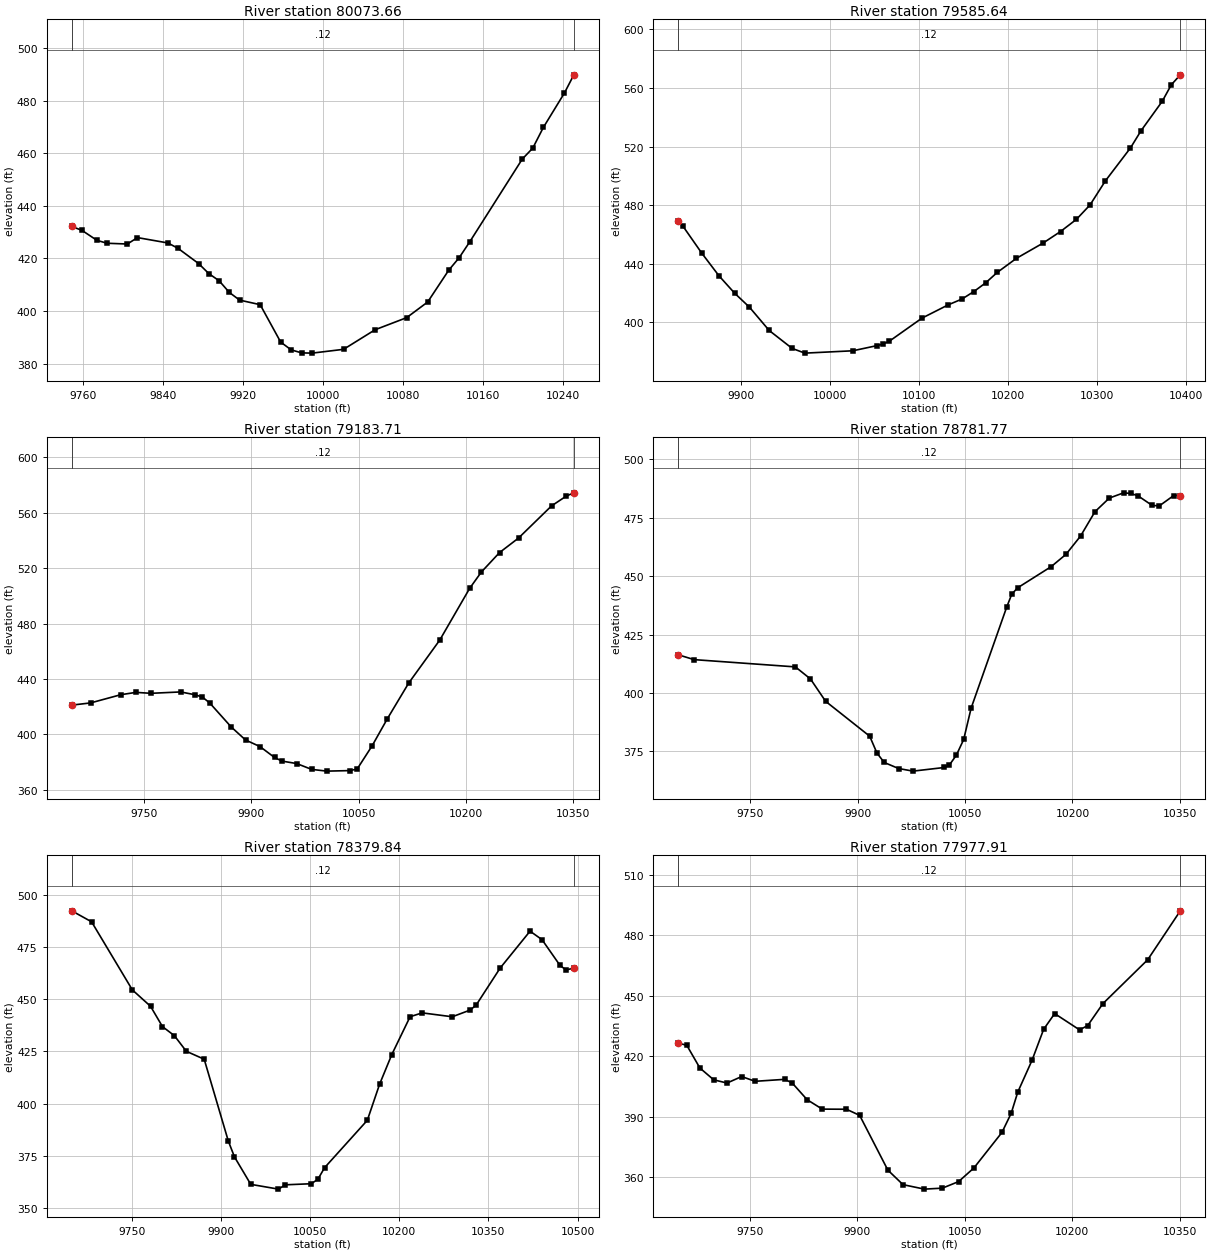
Type RM Length L Ch R = 1 ,80073.66,488.026300,488.026300,488.026300
XS GIS Cut Line= 6
443213.328178395780820.199322585443231.082623066 780926.50114219
443254.020849551781025.643992843443265.861162107781064.288391476
443266.514428379781066.178693881443343.443579904781304.034678523
#Sta/Elev= 30
9749.046432.15989759.195430.68939774.191426.88929784.329 425.7769804.606425.4862
9814.745 427.926 9845.16425.89089855.299423.83619875.808 418.0619886.072414.2261
9896.336411.50839906.601407.04379916.865404.13549937.393402.39929957.921388.1494
9968.368385.20919978.827384.05359989.285383.959110020.78385.405510052.31 392.861
10083.84397.459810104.86403.412910125.88415.507910136.39420.2933 10146.9426.3089
10199.45457.824310209.96462.006910220.47469.833210241.49482.912210250.99489.8789
#Mann= 3 , 0 , 0
9749.046    0.12       09749.046    0.12       010250.99    0.12       0
#XS Ineff= 2 , 0
       0                               0
Bank Sta=9749.046,10250.99
Exp/Cntr=0.3,0.1

Type RM Length L Ch R = 1 ,79585.64,401.931300,401.931300,401.931300
XS GIS Cut Line= 6
442761.796142727781190.660170704442800.990754157781253.006356433
442838.284368545 781298.33574754443007.377460718781484.136666462
443061.399828136781555.725070953443110.494925916781632.094478071
#Sta/Elev= 30
9829.752469.24839834.767465.89519856.103447.33929875.532431.78919892.997 420.024
 9909.77410.3916 9931.94394.50299957.839382.24129972.083379.054310025.87380.6501
10053.38384.213910059.87385.258310067.13387.254310103.57402.9073 10133.1411.9855
10148.64415.966410161.83421.024310175.02426.9125 10188.2434.104510209.79443.7322
10239.58454.0887 10259.3462.006910277.16 470.311 10292.5480.164110309.78496.6116
10337.93 519.05210349.82530.809810373.59550.826710383.75562.072710393.91568.9056
#Mann= 3 , 0 , 0
9829.752    0.12       09829.752    0.12       010393.91    0.12       0
#XS Ineff= 2 , 0
       0                               0
Bank Sta=9829.752,10393.91
Exp/Cntr=0.3,0.1

Type RM Length L Ch R = 1 ,79183.71,401.931400,401.931400,401.931400
XS GIS Cut Line= 6
442584.752227505781240.139867964442539.564282417 781378.04195845
442530.972624754781428.201942184442531.698231633781476.910721113
442546.887914417781549.926740616442660.143446287781915.085999568
#Sta/Elev= 30
9649.104421.16899675.391422.75299717.686428.68939738.834430.35679759.849429.6856
9801.316430.68119821.607428.63199831.753426.95469841.898422.75029871.956405.4375
9892.002396.02399912.235391.2613 9932.58383.39359942.882380.80619963.486379.0223
9984.487374.800810005.66 373.55510037.48373.933810048.03 375.03310069.04391.8697
10090.04411.134410120.16437.114210163.57468.107910205.35505.395310221.65517.1377
10247.09531.1945 10273.7541.703510319.81564.874610340.54571.994210350.99574.3049
#Mann= 3 , 0 , 0
9649.104    0.12       09649.104    0.12       010350.99    0.12       0
#XS Ineff= 2 , 0
       0                               0
Bank Sta=9649.104,10350.99
Exp/Cntr=0.3,0.1

Type RM Length L Ch R = 1 ,78781.77,401.931300,401.931300,401.931300
XS GIS Cut Line= 6
 442573.54403114781225.697225978442531.969019991781290.697681543
442464.426173334781343.705125215442173.925588998781419.792291953
442137.427214441 781499.31727753442133.567571923781644.207332403
#Sta/Elev= 30
9649.143416.38749671.365414.31739812.847411.20789833.912406.04639855.123396.4709
9916.709381.53169926.832374.32769936.956370.29439957.087367.7084  9977.2366.5877
10021.12368.150610027.64369.026810037.83373.430810048.02 380.13610058.45393.5715
10108.03436.707810115.22442.332710123.34445.045310170.37454.145710190.93459.3718
10211.35  467.2110231.42477.620610251.49483.467310271.54485.722310281.54485.4481
10291.54484.454710311.54480.307610321.54480.163210341.55484.569810350.75484.4987
#Mann= 3 , 0 , 0
9649.143    0.12       09649.143    0.12       010350.75    0.12       0
#XS Ineff= 2 , 0
       0                               0
Bank Sta=9649.143,10350.75
Exp/Cntr=0.3,0.1

Type RM Length L Ch R = 1 ,78379.84,401.931400,401.931400,401.931400
XS GIS Cut Line= 6
442127.920038909780798.736460194442089.451842338780922.084767371
442088.351609677781024.532545999442164.673019797781245.521912068
442138.628736645781374.910007372  442110.2082268781618.206993937
#Sta/Elev= 30
9649.152492.32929682.483487.06859751.041454.45399781.649446.60029801.719436.8663
9821.789432.51079841.844425.04269871.906421.23539912.485382.0409 9922.82374.4546
9950.247361.29879996.869359.011210008.28361.0782 10052.1361.596510063.24363.7752
10074.38 369.268 10146.3391.9869 10166.9409.2462 10187.5423.495610218.26441.6102
10238.64443.447210289.16441.575110319.37444.796810329.44447.2016 10369.7464.8941
10420.02 482.58110440.15478.525710470.34466.2241 10480.4464.0206 10493.7464.8665
#Mann= 3 , 0 , 0
9649.152    0.12       09649.152    0.12       0 10493.7    0.12       0
#XS Ineff= 2 , 0
       0                               0
Bank Sta=9649.152,10493.7
Exp/Cntr=0.3,0.1

Type RM Length L Ch R = 1 ,77977.91,401.931300,401.931300,401.931300
XS GIS Cut Line= 6
441880.563323605781194.457419411 441817.78498914781433.814181829
441938.622749645781482.875816522442020.270228822781543.573459744
442066.756028678781616.141787833442100.434074843781739.419064546
#Sta/Elev= 30
9650.386426.5274 9662.31425.42979680.604414.13139699.912408.27439718.443406.6775
9738.855409.90419757.624407.53699799.096408.51849809.464406.66559830.199398.4051
9851.279393.72499885.054393.66069903.487390.61919942.817363.42899963.954356.2036
9993.832353.980810018.87354.468110041.51357.727710062.93364.523910101.93 382.115
10114.86391.627210124.09402.204710143.96417.979510160.15433.365610175.54441.1776
10210.19433.108610221.53435.186110242.78446.1047 10305.3467.914910350.82492.2184
#Mann= 3 , 0 , 0
9650.386    0.12       09650.386    0.12       010350.82    0.12       0
#XS Ineff= 2 , 0
       0                               0
Bank Sta=9650.386,10350.82
Exp/Cntr=0.3,0.1

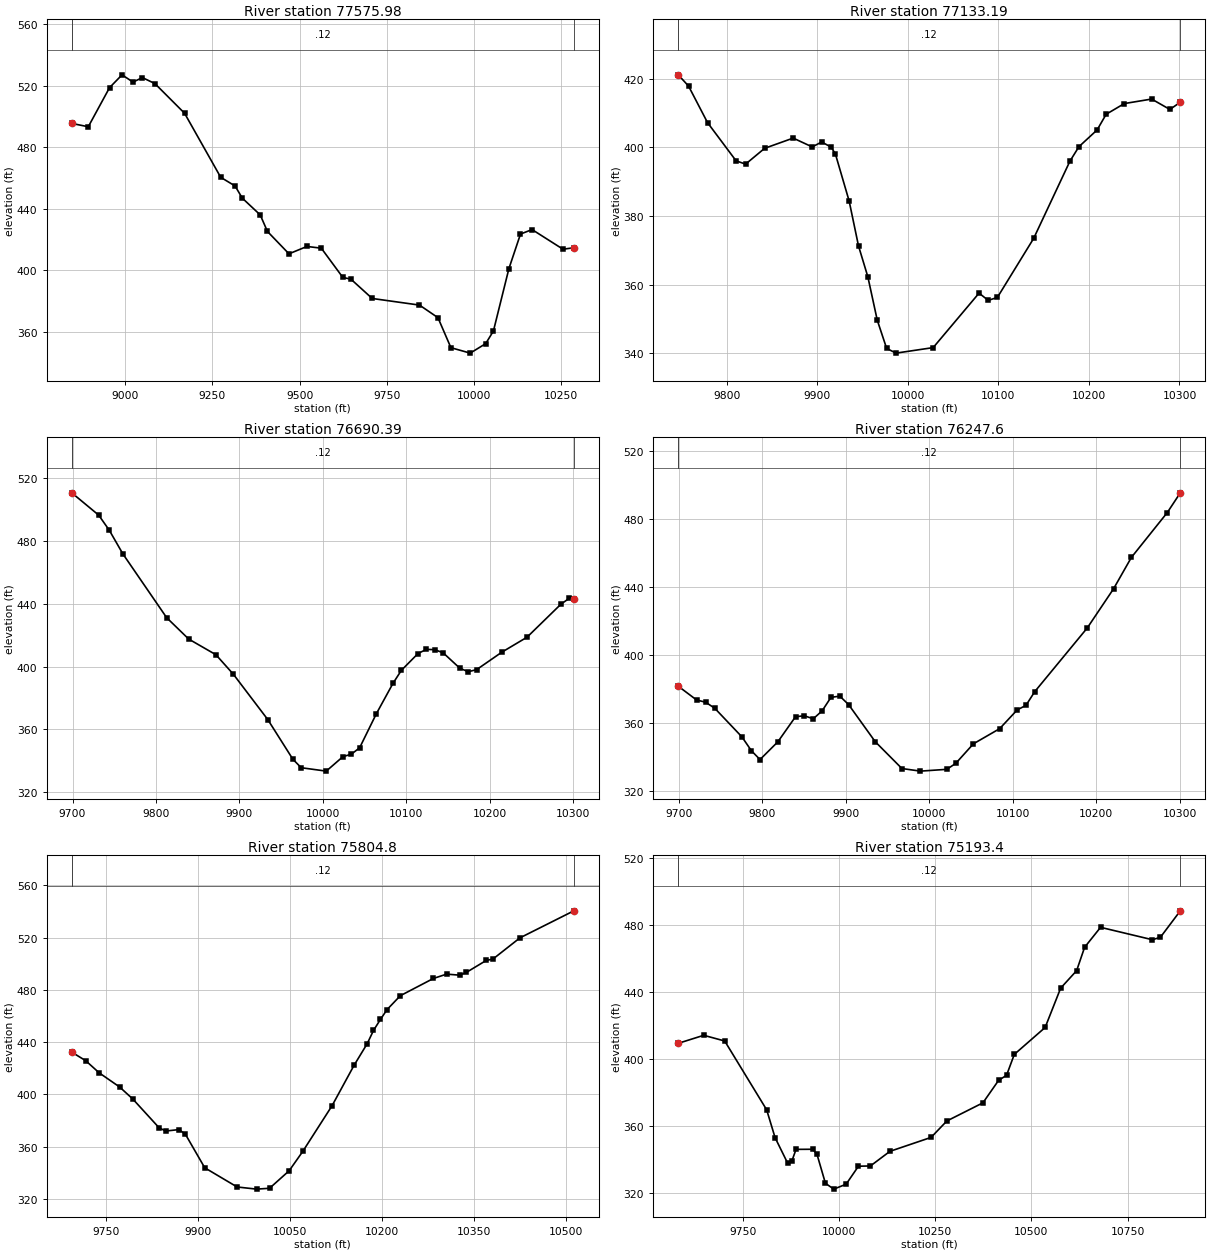
Type RM Length L Ch R = 1 ,77575.98,442.794000,442.794000,442.794000
XS GIS Cut Line= 6
442084.627866834780686.908121139441985.791791856780829.913928926
441925.475435674780954.583215386441773.130624592781521.021580145
441669.873364657781670.650125206441515.607476413781993.012320906
#Sta/Elev= 30
8846.603495.48968893.948493.32988954.913518.7233 8990.75527.06149022.147522.3441
9049.173525.26269085.004521.36689170.116502.07859273.723 460.4899314.929454.8583
9335.531 446.9749387.037436.0645 9407.64425.33749469.447 410.7899520.954415.5815
9562.159414.44889623.966395.43059646.853 394.3739708.088381.78899843.747377.4896
9896.683369.30919933.796349.81769989.226346.284110033.57 352.45410055.74360.6648
10100.09401.143610133.35423.6321 10166.6426.543210255.29413.778810286.35414.7375
#Mann= 3 , 0 , 0
8846.603    0.12       08846.603    0.12       010286.35    0.12       0
#XS Ineff= 2 , 0
       0                               0
Bank Sta=8846.603,10286.35
Exp/Cntr=0.3,0.1

Type RM Length L Ch R = 1 ,77133.19,442.794100,442.794100,442.794100
XS GIS Cut Line= 6
441852.829754591781194.161855057441799.598518997 781359.44163999
441685.965346128781330.910939947441621.393199414781321.064377144
441524.685397416781319.786907002441423.549838603781329.555664986
#Sta/Elev= 30
9746.387421.11749757.774417.83999778.785407.16949810.303396.04499820.809395.0922
 9841.82399.69999873.338402.6772 9894.35400.10799904.855401.54049915.361400.0242
9920.028397.99779935.139384.3521 9945.49371.25579955.841362.22399966.192349.6187
9976.543341.39079986.894340.001710027.95341.609610078.65357.492310088.76355.3787
10098.88356.235810138.96373.442610178.98395.934610188.98400.179810209.01405.0475
10219.03409.622910239.08412.740810269.27414.0579 10289.4411.028710300.93413.1294
#Mann= 3 , 0 , 0
9746.387    0.12       09746.387    0.12       010300.93    0.12       0
#XS Ineff= 2 , 0
       0                               0
Bank Sta=9746.387,10300.93
Exp/Cntr=0.3,0.1

Type RM Length L Ch R = 1 ,76690.39,442.794000,442.794000,442.794000
XS GIS Cut Line= 6
441889.564616883780845.816582042441798.718395027780913.912863552
 441715.01886067780948.027382889441653.651829613780956.553293722
441466.789904949780958.518174827441319.766152997780978.874493886
#Sta/Elev= 30
9699.122510.81929731.387496.59769744.133486.92879760.329471.93179812.878431.2209
9839.265417.60559871.914407.61039892.966395.07569934.045366.2931 9964.16340.9834
9974.165335.571610004.17333.403210024.17342.633410034.17344.171710044.17348.2694
10064.17369.933310084.18389.373110094.19 397.64510114.21408.389310124.22411.0283
10134.22410.832610144.23408.852810164.31399.005910174.37396.767610184.42398.1048
 10214.6409.213910244.88418.794110285.49439.836710295.64443.651110300.96443.3681
#Mann= 3 , 0 , 0
9699.122    0.12       09699.122    0.12       010300.96    0.12       0
#XS Ineff= 2 , 0
       0                               0
Bank Sta=9699.122,10300.96
Exp/Cntr=0.3,0.1

Type RM Length L Ch R = 1 , 76247.6,442.794000,442.794000,442.794000
XS GIS Cut Line= 6
 441855.27716239780410.776485927441759.772274427780451.220529374
441613.101238802780503.551751348441542.501353287780531.713574688
441359.902840175780590.438562779441290.486551395780617.909315782
#Sta/Elev= 30
9699.036381.43349721.056373.31049731.916 371.9959742.776368.46899775.355351.6145
9786.799343.41019797.074338.23779818.436348.6803 9839.67363.48349850.288 364.002
9860.905362.24349871.523366.9113 9882.14374.87659892.758375.57469903.272370.6113
9935.227 348.7489967.199332.96069989.411331.431710021.04332.4898 10031.8336.0295
10052.87347.501510084.39356.436810105.39367.4702 10115.9370.1454 10126.4378.2039
10189.43415.747910220.94438.804910242.33457.284710285.34483.668910300.95495.2862
#Mann= 3 , 0 , 0
9699.036    0.12       09699.036    0.12       010300.95    0.12       0
#XS Ineff= 2 , 0
       09902.261                       0
Bank Sta=9699.036,10300.95
Exp/Cntr=0.3,0.1

Type RM Length L Ch R = 1 , 75804.8,611.404300,611.404300,611.404300
XS GIS Cut Line= 6
441715.672929406779991.226774246  441556.4305574780059.254869372
441389.034962624780116.657705396441330.921223193780149.458701402
441311.115887672780174.802514926441171.857476413780517.317876458
#Sta/Elev= 30
9694.386 432.2729717.179425.72129739.229416.40189772.305405.66849793.883396.4619
9836.899374.39479847.653 371.9059869.133373.00939879.691369.53419911.365343.7895
9964.171329.10869995.929327.4622 10017.1328.118110049.06341.503910071.23356.2653
10119.24391.403510154.88422.116710176.47 438.79410186.66448.849910198.06 457.341
10208.85464.855510230.44475.452510284.42488.664110306.01 491.979 10327.6491.1761
10338.39493.349510370.78502.484810381.57503.494610425.62 519.72210513.61 540.418
#Mann= 3 , 0 , 0
9694.386    0.12       09694.386    0.12       010513.61    0.12       0
#XS Ineff= 2 , 0
       0                               0
Bank Sta=9694.386,10513.61
Exp/Cntr=0.3,0.1

Type RM Length L Ch R = 1 , 75193.4,1180.002400,1180.002400,1180.002400
XS GIS Cut Line= 6
441296.664569199779224.211127385441104.067899495779690.585042104
441177.628019542779871.539830551441207.786712289 780020.33311978
441203.107476413780149.262320891  441119.7741431780454.817876458
#Sta/Elev= 30
9582.905409.23589649.137414.02559703.615410.62219812.569 369.565 9834.36353.0082
9867.047 337.7569877.942338.98899888.838345.97589932.419346.04419943.315342.9937
9965.106325.7722 9986.83322.258310018.93325.1993 10050.9335.923910082.04336.0823
10132.68344.798610239.56353.1215 10280.5362.909610374.23373.744910415.01387.1744
10435.56390.153910455.71402.6391 10535.8418.700110576.08 442.15810617.54452.5796
10638.27466.516810679.73478.434510814.48471.030710835.21 472.51910886.84488.2796
#Mann= 3 , 0 , 0
9582.905    0.12       09582.905    0.12       010886.84    0.12       0
#XS Ineff= 2 , 0
       0                10163.89       0
Bank Sta=9582.905,10886.84
Exp/Cntr=0.3,0.1

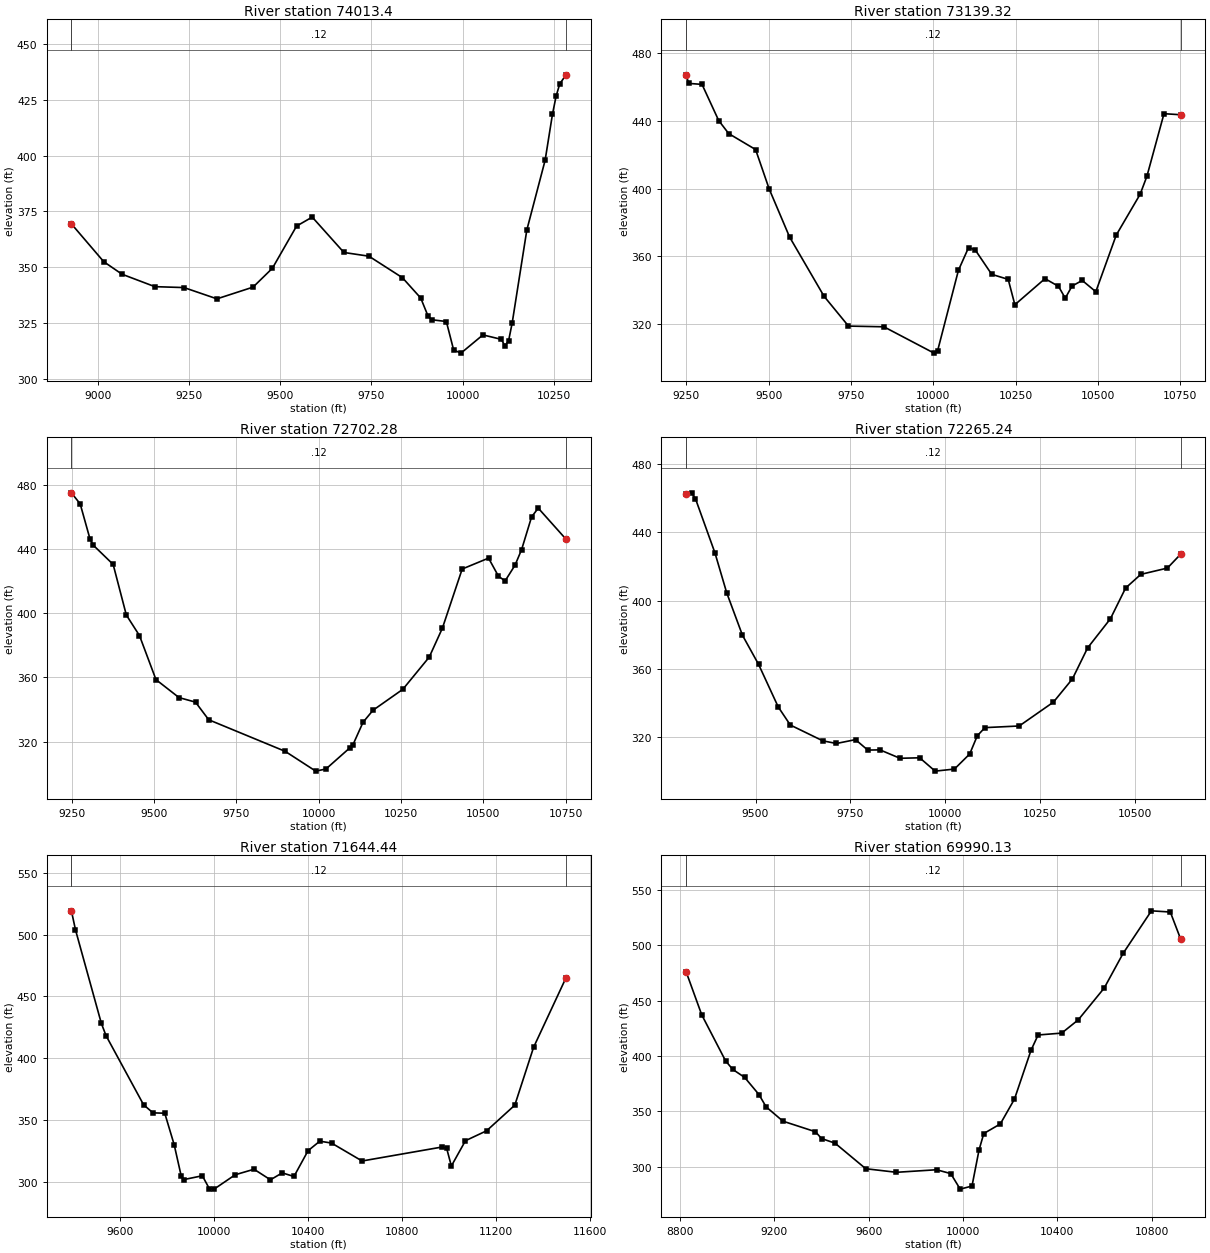
Type RM Length L Ch R = 1 , 74013.4,874.077800,874.077800,874.077800
XS GIS Cut Line= 6
440602.829754621779186.349355042440587.638782352779527.061160624
 440598.48947683779672.460466161 440761.60474807779875.391374394
440802.457859188 779955.03800416440758.663031965780472.178987548
#Sta/Elev= 30
8927.195369.44489015.934352.54459065.984 346.9579156.073341.39569236.153340.9852
9326.346335.94779425.319341.18359478.415349.61379544.729368.46239587.649 372.481
9674.542356.66979743.145355.00919835.023345.40029885.202336.31469905.274328.2672
9915.309326.61089955.453325.81859975.524313.08629995.596311.692910055.81319.8341
10105.99317.863910116.03315.000210126.06317.1098 10136.1325.224110176.24366.7433
10226.42397.888610246.49418.412610256.53426.535910266.56432.0393 10283.8436.0525
#Mann= 3 , 0 , 0
8927.195    0.12       08927.195    0.12       0 10283.8    0.12       0
#XS Ineff= 2 , 0
       09675.039                       0
Bank Sta=8927.195,10283.8
Exp/Cntr=0.3,0.1

Type RM Length L Ch R = 1 ,73139.32,437.038900,437.038900,437.038900
XS GIS Cut Line= 6
439991.871061774779206.868747015440062.186454004779550.621330719
440219.709808468 779954.87846191440241.675326037780058.690517126
440224.413326458780239.547522086440118.456220774780653.980541692
#Sta/Elev= 30
9249.053467.29079257.263462.22429297.652461.63249348.203440.27779378.689432.5392
9460.276423.10989501.257399.93929563.423371.40989668.037336.37939742.275 318.736
9849.815 318.315 10002.1302.744410012.93304.173810076.15351.752310106.78365.1146
10126.98363.793610177.13349.333310227.23346.353510247.41331.358510338.89346.7764
 10379.9342.249210400.42  335.2310421.03342.396810451.96345.727110493.19339.0552
10555.23 372.54910627.69396.6532 10648.4407.358510700.16444.311510750.86443.6888
#Mann= 3 , 0 , 0
9249.053    0.12       09249.053    0.12       010750.86    0.12       0
#XS Ineff= 2 , 0
       09802.606        10107.87       0
Bank Sta=9249.053,10750.86
Exp/Cntr=0.3,0.1

Type RM Length L Ch R = 1 ,72702.28,437.038900,437.038900,437.038900
XS GIS Cut Line= 6
439728.440524263779278.312604438439731.231451137779755.646035189
439810.393656246780147.382946711 439827.48971601780309.705442744
439822.665073736780542.291807977439796.604813769780768.744604911
#Sta/Elev= 30
9249.048475.07549275.749468.16069305.764446.12179315.769442.3747  9375.8430.4524
9415.807 398.918 9455.81386.07139505.814358.63789575.827347.43599625.836344.6173
9665.921333.62469898.107313.94379990.902301.603410021.96302.939110093.84315.9983
10104.04 318.10610134.58332.078110164.87339.564810255.38 352.61410335.48372.6752
10375.49390.746210435.54427.582310515.63434.376510545.73423.080910565.82420.1613
10595.95429.964610616.03439.735810646.28460.078110666.45 465.53810750.91446.1306
#Mann= 3 , 0 , 0
9249.048    0.12       09249.048    0.12       010750.91    0.12       0
#XS Ineff= 2 , 0
       0                               0
Bank Sta=9249.048,10750.91
Exp/Cntr=0.3,0.1

Type RM Length L Ch R = 1 ,72265.24,620.804600,620.804600,620.804600
XS GIS Cut Line= 6
439553.265010297779370.849390954439490.604205638779601.283973351
439378.447080582779896.660109565439349.931457371780022.525193214
 439328.72931233780295.503144696439340.360647053780639.925163805
#Sta/Elev= 30
9316.919462.52269331.451463.05979341.721459.65399393.069427.91369424.072404.5266
9465.554379.66869508.037362.60889559.778337.69289591.599327.11769677.235317.8631
9712.988316.3163 9763.28318.56659795.548312.44829827.618312.57879880.481307.6446
 9932.29307.93559973.002300.128410023.76301.335110063.95310.146710084.05320.8416
10104.14325.599710194.44326.560410284.49340.5293 10334.5354.110610374.51372.2635
10434.56389.3243 10474.6407.325810514.63415.317810584.69419.011110619.64427.1531
#Mann= 3 , 0 , 0
9316.919    0.12       09316.919    0.12       010619.64    0.12       0
#XS Ineff= 2 , 0
       0                10101.95       0
Bank Sta=9316.919,10619.64
Exp/Cntr=0.3,0.1

Type RM Length L Ch R = 1 ,71644.44,1654.303100,1654.303100,1654.303100
XS GIS Cut Line= 3
438919.216837794779017.635655716438891.493616462780102.264346346
438863.661282241781123.191211298
#Sta/Elev= 30
  9392.1 519.417 9409.47504.03069519.506428.28649539.513418.26799699.565362.1959
9739.578355.67769789.594355.37629829.607 329.9529859.617304.5582 9869.62301.5452
9949.647304.69099979.656294.14539999.663293.858910089.69305.507710169.72309.9744
10239.74301.414610289.76307.031410339.77 304.11310399.79324.994910449.81332.7221
10499.83331.185710629.88316.6598   10970327.973810990.01326.890911010.02312.5999
11070.04333.101411160.07341.142811280.12361.915411360.15408.798411498.39465.2653
#Mann= 3 , 0 , 0
  9392.1    0.12       0  9392.1    0.12       011498.39    0.12       0
#XS Ineff= 2 , 0
       0                10479.88       0
Bank Sta=9392.1,11498.39
Exp/Cntr=0.3,0.1

Type RM Length L Ch R = 1 ,69990.13,450.081000,450.081000,450.081000
XS GIS Cut Line= 4
438394.965838671779189.069901913438335.938060939779584.903235242
438403.506012678779772.885173872438485.243616462781268.931013018
#Sta/Elev= 30
 8825.49476.24168892.149437.08368993.255395.50699023.586 387.7779074.139380.5467
9134.803365.07529165.134353.95439236.429340.99689374.572331.42879400.309325.2892
9457.619321.10829587.813298.02079718.007294.7843 9888.26297.0906 9948.35293.6198
 9988.41279.577810038.48282.352110068.53 315.07810088.56329.845610158.66338.4767
10218.75360.976610288.86405.0639 10318.9418.880210419.05420.582410489.16432.5484
10599.32461.298210679.44492.609910799.62 531.08410879.74530.011610923.73505.4874
#Mann= 3 , 0 , 0
 8825.49    0.12       0 8825.49    0.12       010923.73    0.12       0
#XS Ineff= 2 , 0
       0                10115.14       0
Bank Sta=8825.49,10923.73
Exp/Cntr=0.3,0.1

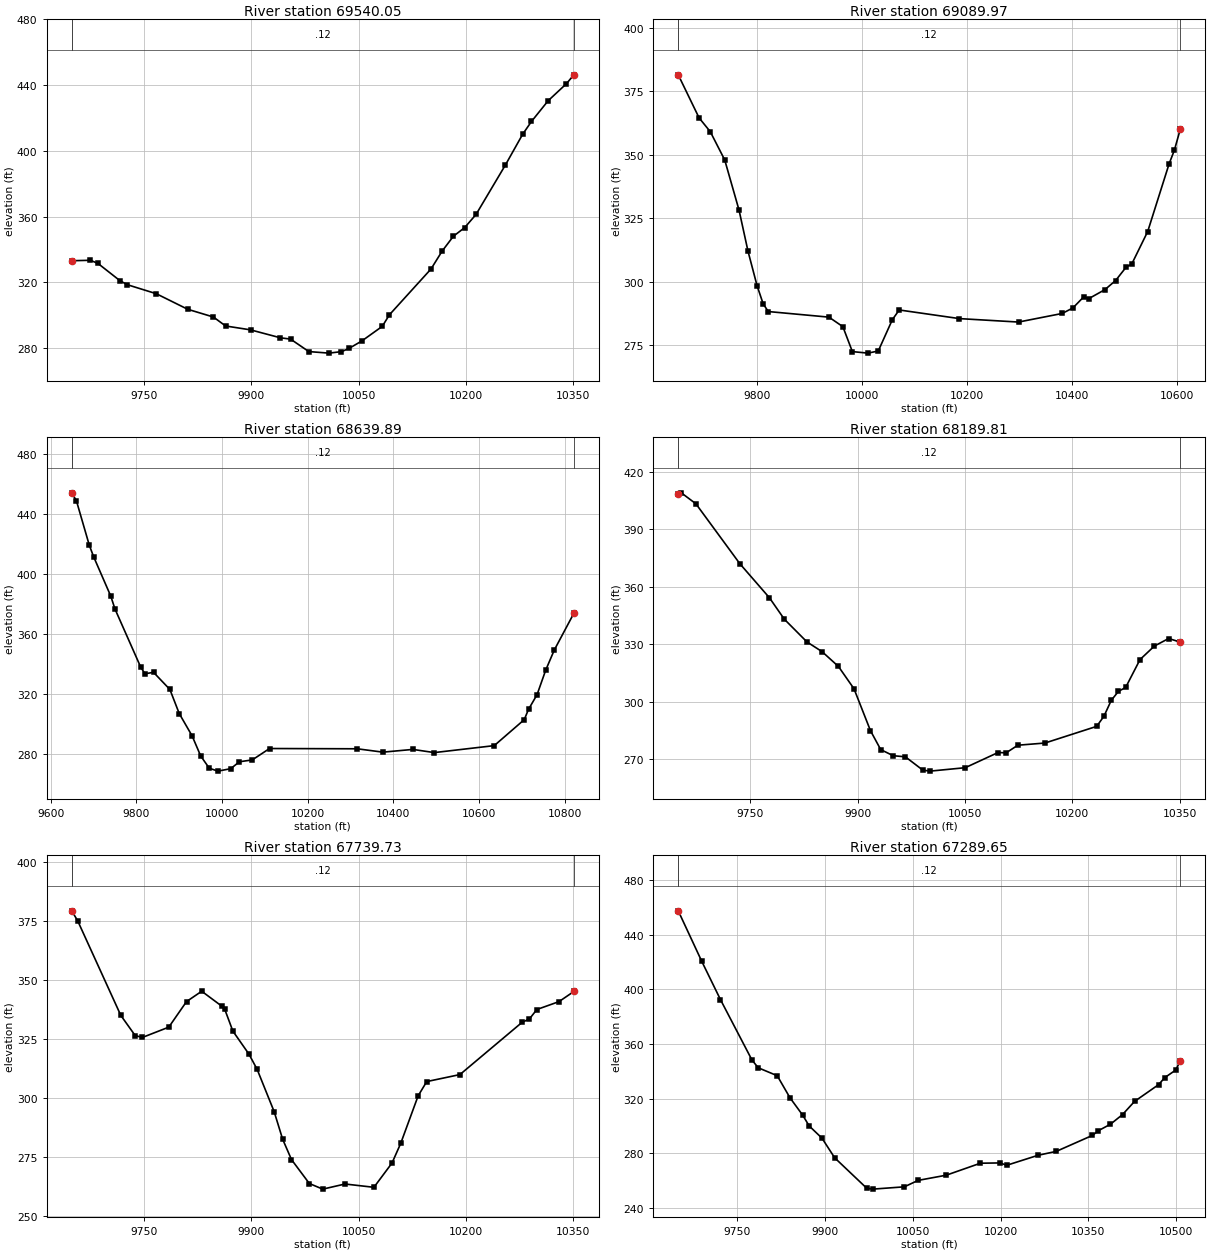
Type RM Length L Ch R = 1 ,69540.05,450.081000,450.081000,450.081000
XS GIS Cut Line= 6
 438197.61466912779810.894950969438218.594256966779884.860514099
438211.109633036779931.393004858438185.687678888779981.176196981
 437954.60369698780226.772659354437844.355173824780373.442997076
#Sta/Elev= 30
9649.057333.1727 9675.19 333.4389685.678331.52059716.469321.00989726.552318.5982
9767.127313.11429811.097303.63149847.049298.91189864.125293.45779898.926291.1028
9940.755286.26479954.958285.46669980.447277.877110008.56276.937510026.11277.8381
 10036.6279.786210054.64284.362210083.18 293.24710093.08300.250610151.32328.1719
10166.77339.002510182.56 348.07310198.41353.361310214.25 361.35610255.05391.2679
 10279.5410.209510291.73417.934710315.06430.553410340.63440.931210350.95446.3097
#Mann= 3 , 0 , 0
9649.057    0.12       09649.057    0.12       010350.95    0.12       0
#XS Ineff= 2 , 0
       0                               0
Bank Sta=9649.057,10350.95
Exp/Cntr=0.3,0.1

Type RM Length L Ch R = 1 ,69089.97,450.081000,450.081000,450.081000
XS GIS Cut Line= 6
437914.424809784779516.898798123 437889.95510599779590.200998634
 437849.53533107 779666.49356842437622.655861974779942.212732598
437559.218985677780053.340041578437498.157565832780356.002228156
#Sta/Elev= 30
9649.055381.53979688.904364.55449710.204359.12969737.756348.00159765.063328.2341
9782.246311.98149799.472298.44959811.067291.30839820.843 288.2489936.631286.0434
9963.188 282.2969981.338272.459910011.04271.860410030.74272.697210057.69285.0652
10070.73  288.8710185.61285.465910298.38284.105410381.68287.491110402.09289.6553
10422.49293.962610432.69293.3584 10463.3296.8884 10483.7300.4758 10504.1305.8458
 10514.3306.895810544.91319.788110585.71346.440310595.92351.901910607.14 360.151
#Mann= 3 , 0 , 0
9649.055    0.12       09649.055    0.12       010607.14    0.12       0
#XS Ineff= 2 , 0
       0                10166.21       0
Bank Sta=9649.055,10607.14
Exp/Cntr=0.3,0.1

Type RM Length L Ch R = 1 ,68639.89,450.081000,450.081000,450.081000
XS GIS Cut Line= 6
437390.280557871779184.076084062437390.145394534779413.186342701
437377.422248662779607.278586775437385.785929501779661.967299029
437421.159243673 779801.34247452437424.444337934780350.845882818
#Sta/Elev= 30
 9649.03453.94029659.954448.57739689.956419.09579699.956411.51669739.958 385.333
9749.959  376.659809.963338.02919819.964333.57649839.966334.55089878.155323.1445
9900.009307.10789930.065292.27229950.102278.9062 9970.14270.76629990.177  268.83
10020.28270.462110040.42275.058710070.49276.276610110.87283.868410315.62 283.688
10375.62281.450710445.62283.272110495.62281.158810635.63285.794210705.63303.0571
10715.63309.920710735.63319.720610755.63335.898310775.63349.280410821.48373.8121
#Mann= 3 , 0 , 0
 9649.03    0.12       0 9649.03    0.12       010821.48    0.12       0
#XS Ineff= 2 , 0
       0                10322.01       0
Bank Sta=9649.03,10821.48
Exp/Cntr=0.3,0.1

Type RM Length L Ch R = 1 ,68189.81,450.081000,450.081000,450.081000
XS GIS Cut Line= 6
437014.695023096779550.802891485437069.161185686779753.378354717
437180.152353978779930.168576612437219.816585708780016.759820329
437241.240062379780107.115455263437247.061999217780201.268921776
#Sta/Elev= 30
9649.051408.38459653.335409.07849673.751 403.3449735.266371.98629776.493354.2437
9797.335 343.0329828.927331.17079850.204326.04189872.993318.32969894.779306.6445
9917.758284.7743 9932.08274.87389949.535271.67849966.562271.09879990.964264.1406
   10001263.617610050.25265.409310096.17273.343510107.44273.180510123.78277.1594
10161.64278.299110234.02287.021210244.19292.341710254.35300.587810264.43 305.327
10274.47307.334310294.57 321.92210314.63328.984210334.63332.937110350.91331.0402
#Mann= 3 , 0 , 0
9649.051    0.12       09649.051    0.12       010350.91    0.12       0
#XS Ineff= 2 , 0
       0                10118.06       0
Bank Sta=9649.051,10350.91
Exp/Cntr=0.3,0.1

Type RM Length L Ch R = 1 ,67739.73,450.081000,450.081000,450.081000
XS GIS Cut Line= 6
436911.202312907779386.640817968436897.693112418779510.807218435
436871.381192538779591.754571457436828.750293146779666.092419392
436685.842567145779860.954676716436633.228910444780015.309453217
#Sta/Elev= 30
9649.116379.32829657.498375.02179717.659335.04919737.828326.47779747.971325.7293
9784.726330.07249809.503340.89139830.766345.27919859.379338.83139863.029337.5756
9874.277328.41419896.772318.65529908.262 312.173    9932294.3045 9943.87282.6277
9956.251273.98389981.199 263.8599999.956261.4821 10031.1263.651510071.47262.2549
10096.74272.529110108.93280.8574 10133.3300.998110145.28307.024810191.69309.9893
10278.49332.094210288.85333.555610299.22337.540810330.21 340.88810350.93345.1704
#Mann= 3 , 0 , 0
9649.116    0.12       09649.116    0.12       010350.93    0.12       0
#XS Ineff= 2 , 0
       0                               0
Bank Sta=9649.116,10350.93
Exp/Cntr=0.3,0.1

Type RM Length L Ch R = 1 ,67289.65,450.081000,450.081000,450.081000
XS GIS Cut Line= 6
436255.376456231779227.296005756436377.742578566779525.291983142
436390.722591758779568.633495942436487.668824255779730.776770577
436511.899166048 779793.31738396436566.805449039780020.984771714
#Sta/Elev= 30
9649.066457.45449689.208420.51949721.149392.5152 9774.87348.38139785.638 342.573
9818.208336.74979840.035320.57039861.862 307.7859872.776 299.9829894.603291.0691
9916.431276.62159970.999254.43749981.463253.7147 10035.4255.398110058.97260.1172
10106.98263.908110165.39272.685410199.21272.899210210.25271.157610263.87 278.488
10295.09281.357910356.81293.0545 10367.1296.529210387.67 301.24810408.25308.3013
10428.82317.948410469.97330.235410480.25335.300110499.28340.927910506.98347.7313
#Mann= 3 , 0 , 0
9649.066    0.12       09649.066    0.12       010506.98    0.12       0
#XS Ineff= 2 , 0
       0                               0
Bank Sta=9649.066,10506.98
Exp/Cntr=0.3,0.1

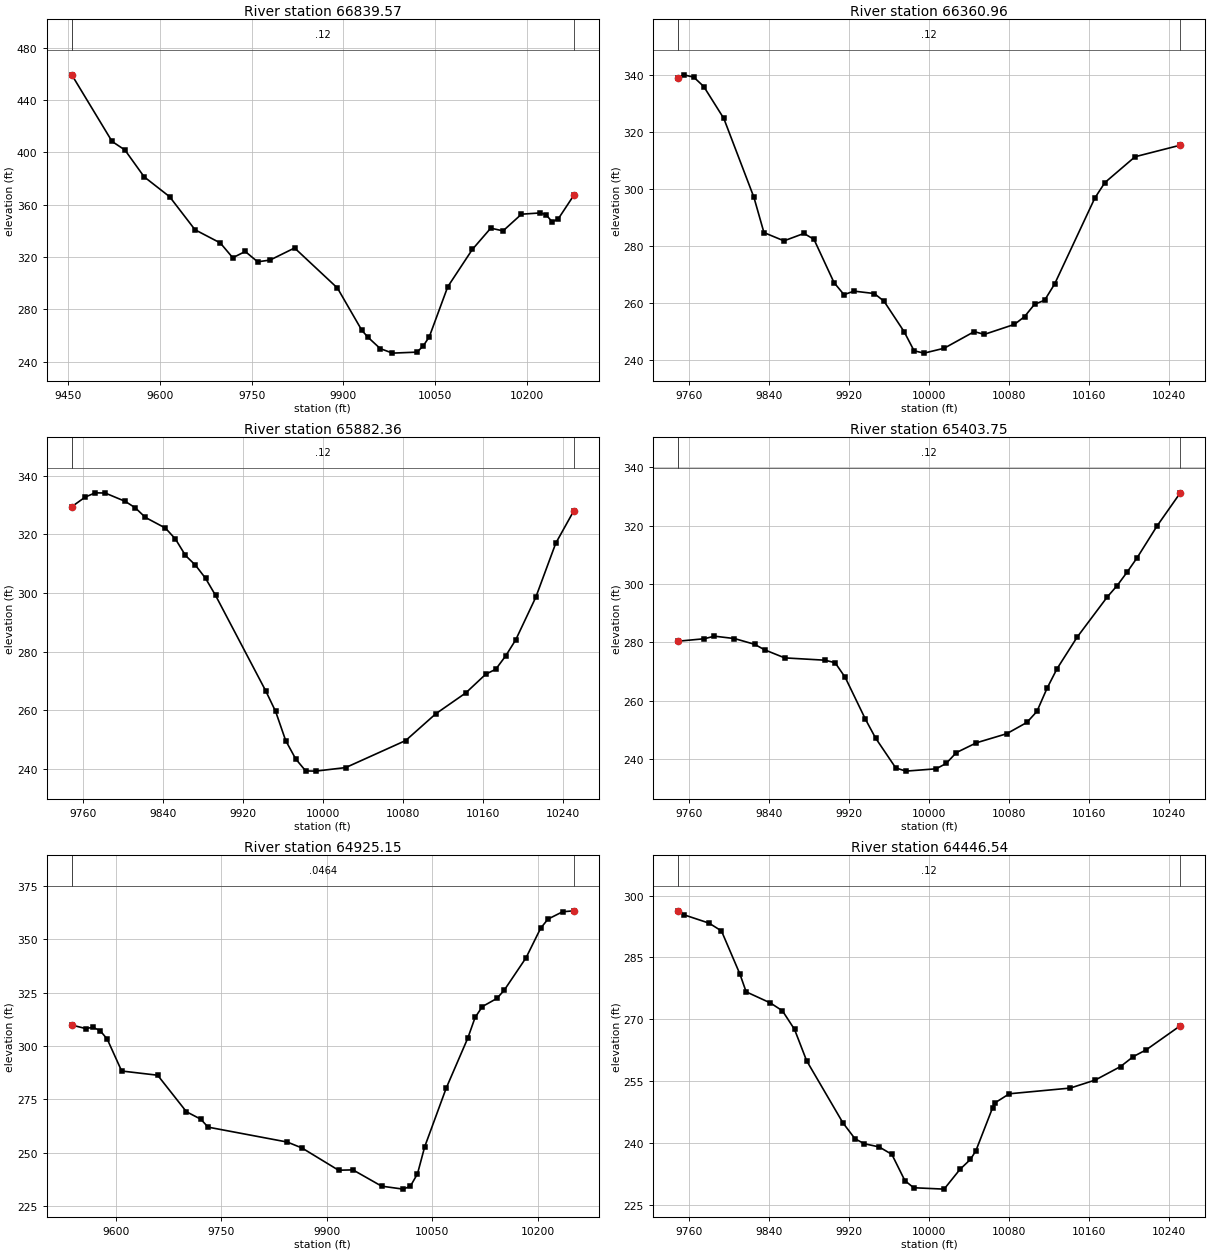
Type RM Length L Ch R = 1 ,66839.57,478.604800,478.604800,478.604800
XS GIS Cut Line= 6
436121.081641853779412.146100913436186.274796546779629.904247304
436202.777191579779714.705714305436207.869150668 779760.72809418
436208.992027223 779902.54921635436179.886990309780220.225862553
#Sta/Elev= 30
 9455.75459.29399521.662408.38319542.635401.87229574.094  381.369615.785366.1399
9657.268 340.9169698.545330.85329719.013  319.529739.396324.31979759.673316.4326
 9779.87317.72819820.096326.98379890.146296.38799930.146264.01089940.151258.7504
9960.165250.10099980.202246.6423 10020.3247.408910030.35252.0629 10040.4259.1342
10070.54297.348710110.73325.852810140.87  342.1410160.97340.054410191.11352.8009
10221.26353.7549 10231.3352.450210241.35346.8677 10251.4349.346310276.75367.2709
#Mann= 3 , 0 , 0
 9455.75    0.12       0 9455.75    0.12       010276.75    0.12       0
#XS Ineff= 2 , 0
       0                               0
Bank Sta=9455.75,10276.75
Exp/Cntr=0.3,0.1

Type RM Length L Ch R = 1 ,66360.96,478.604700,478.604700,478.604700
XS GIS Cut Line= 6
435727.270616308779649.560639632435734.538157143779745.363787488
435734.413698805779845.298181954435731.308360508779899.145659724
435726.242415792779960.270679983 435707.46302601780150.006497686
#Sta/Elev= 30
 9749.05 339.0729754.505340.09719764.534339.29289774.563 335.996 9794.62324.7914
9824.706297.13899834.735284.77659854.765281.87579874.765  284.489884.765282.3957
9904.765267.26459914.765262.99529924.765264.24719945.063263.39919954.781260.7062
9974.814250.05819984.831243.32269994.847 242.50210014.91244.216310045.01250.0461
10055.05249.073310085.18252.582310095.23255.290610105.28259.628610115.33 261.043
10125.38266.765810165.58 296.91310175.62302.321610205.77311.3731   10251315.4283
#Mann= 3 , 0 , 0
 9749.05    0.12       0 9749.05    0.12       0   10251    0.12       0
#XS Ineff= 2 , 0
       0                               0
Bank Sta=9749.05,10251
Exp/Cntr=0.3,0.1

Type RM Length L Ch R = 1 ,65882.36,478.604800,478.604800,478.604800
XS GIS Cut Line= 6
435236.971837908779641.652237722435247.070790523779775.643974604
435252.015681836779865.968821191435252.914152595 779893.11762897
435256.248571046780020.074114513 435256.45532764780143.067717797
#Sta/Elev= 30
9749.004329.4812 9762.39332.75069772.418334.21239782.447334.13859802.504331.2895
9812.532329.0919 9822.56325.83329842.617322.18759852.645318.45249862.674312.8492
9872.702  309.51 9882.73 305.0679892.746299.22039942.821266.70669952.836259.6036
9962.851249.70699972.866243.43289982.873239.32519992.878239.257610022.89240.4679
10082.91249.706610112.92258.816210142.93265.941810162.93 272.32910172.93274.0222
10182.93278.610310192.93284.085410212.93 298.56810232.93317.035410250.99328.0949
#Mann= 3 , 0 , 0
9749.004    0.12       09749.004    0.12       010250.99    0.12       0
#XS Ineff= 2 , 0
       0                               0
Bank Sta=9749.004,10250.99
Exp/Cntr=0.3,0.1

Type RM Length L Ch R = 1 ,65403.75,478.604700,478.604700,478.604700
XS GIS Cut Line= 6
434746.253920211779679.061440098434758.583017852779801.240296344
434776.221902312 779929.21597873434788.413134231780023.823010058
434794.935491507780094.075015399 434800.04398641780177.962804341
#Sta/Elev= 30
9749.015280.43939775.085281.27559785.136282.15989805.238281.34449825.339279.3739
 9835.39 277.4839855.492274.72249895.798273.92889905.893273.05969915.987 268.017
9936.176253.7124 9946.27247.29569966.459237.05349976.553235.943510006.83236.7352
10016.91238.5671   10027242.273710047.16245.650410077.41248.750510097.57252.6154
10107.61256.383410117.66264.2501 10127.7270.987810147.79281.799310177.89295.5571
10187.91 299.50310197.93304.157810207.94309.087510227.98320.022610250.99331.2467
#Mann= 3 , 0 , 0
9749.015    0.12       09749.015    0.12       010250.99    0.12       0
#XS Ineff= 2 , 0
       0                               0
Bank Sta=9749.015,10250.99
Exp/Cntr=0.3,0.1

Type RM Length L Ch R = 1 ,64925.15,478.604800,478.604800,478.604800
XS GIS Cut Line= 6
 434403.53951028779535.689728141434342.813797355779821.257209986
434324.739671409779882.826607481434315.546235681779921.594102412
434284.158505023780080.082125902434243.210571229780230.256361067
#Sta/Elev= 30
9537.774309.77889557.516308.1197 9567.74 308.7049577.963307.18799588.187 303.148
9608.634288.24719659.752 286.2789700.647269.17769721.094265.68549731.317261.9784
 9844.05254.97679864.894252.19479916.683241.80449937.203241.95749977.905234.3419
10008.47232.947410018.67234.254210028.88240.125510039.09252.750110069.71280.2599
10100.38303.680210110.69313.308710121.01 318.41410141.63322.227710151.95326.0136
10183.09341.2667 10203.9355.1343 10214.3359.382610235.11362.814110250.99363.2447
#Mann= 3 , 0 , 0
9537.774  0.0464       09537.774  0.0464       010250.99  0.0464       0
#XS Ineff= 2 , 0
       0 9824.55                       0
Bank Sta=9537.774,10250.99
Exp/Cntr=0.3,0.1

Type RM Length L Ch R = 1 ,64446.54,478.604700,478.604700,478.604700
XS GIS Cut Line= 6
434179.877231751779508.604975839434128.403123897  779546.2562149
 434011.28021741779625.879667071 433944.72523178779681.958140989
433835.001756636779763.842486566433778.471501823779809.381340942
#Sta/Elev= 30
9749.043296.28279755.086295.29389779.865293.29379792.255291.4039 9810.69280.9413
9816.933276.62469841.117273.93049853.209272.02049865.301267.50949877.393259.9016
9913.669244.83219925.761240.95539935.091239.75679949.945238.97669962.607237.1763
9975.608230.81179984.364229.076610014.84228.739910030.75233.550310041.12235.9417
10046.56238.023210063.28 248.46310066.09249.7369   10080251.879910140.96253.2677
10165.91255.210410191.23258.490310204.07260.916710216.91 262.55310250.98 268.399
#Mann= 3 , 0 , 0
9749.043    0.12       09749.043    0.12       010250.98    0.12       0
#XS Ineff= 2 , 0
       09839.787                       0
Bank Sta=9749.043,10250.98
Exp/Cntr=0.3,0.1

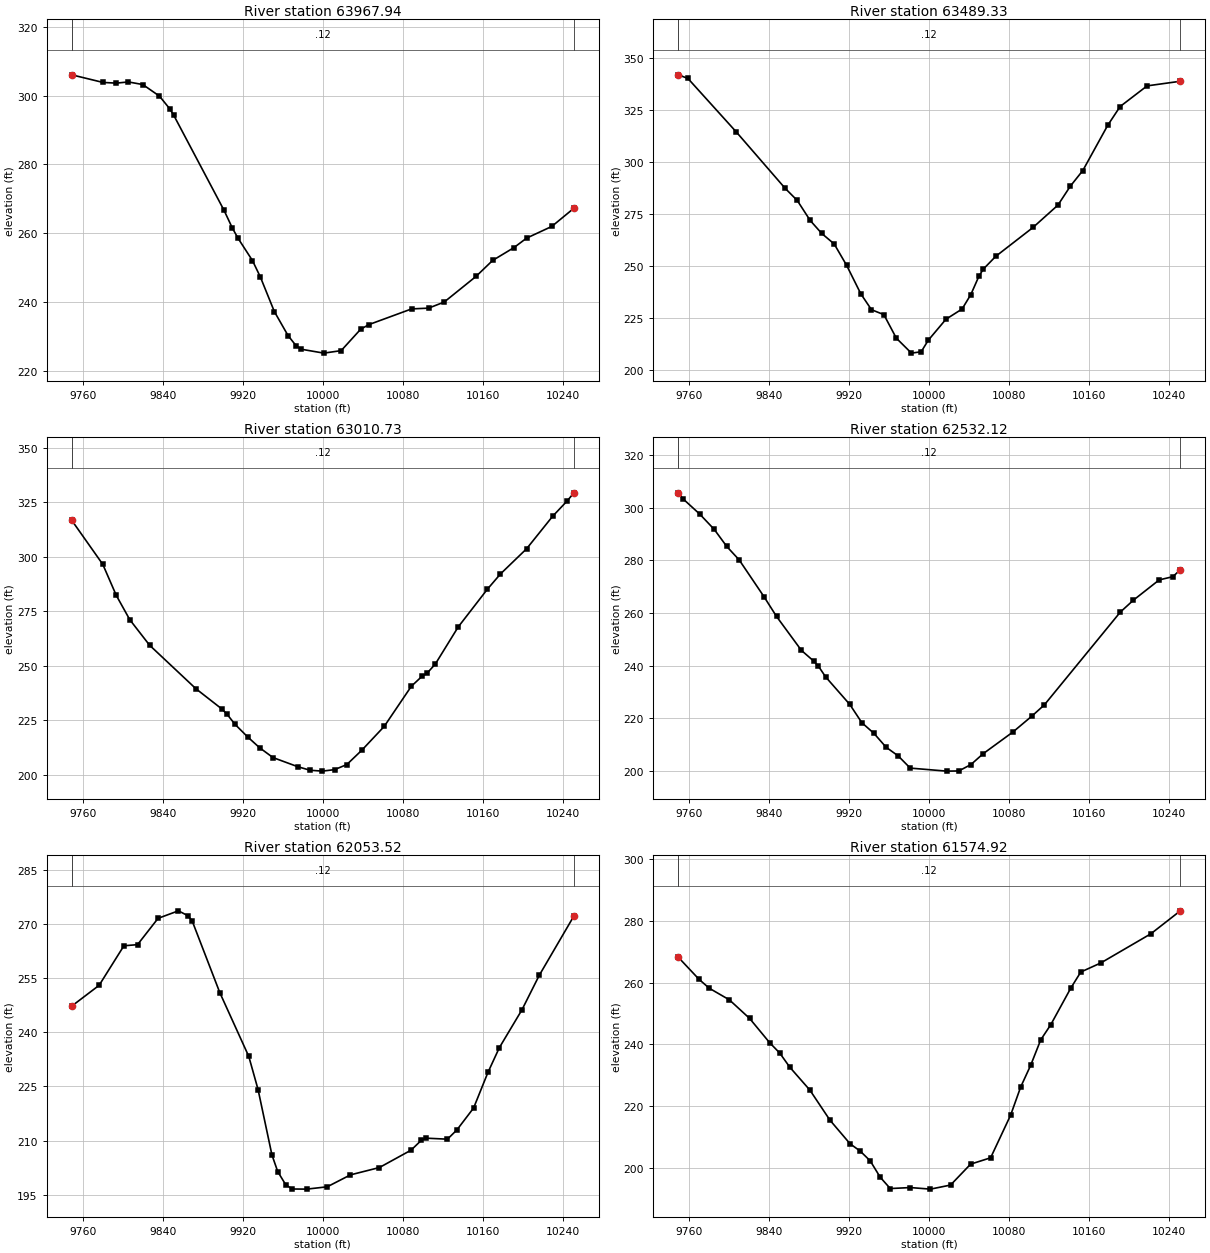
Type RM Length L Ch R = 1 ,63967.94,478.604800,478.604800,478.604800
XS GIS Cut Line= 6
433902.076459572779071.379950169433797.292875547779188.699287172
433700.818421485779278.010271309433671.467802699779308.221293341
433632.527590767779355.075300009433565.632346449779442.510643816
#Sta/Elev= 30
9749.016306.03089780.284303.81659793.522303.62149805.598303.96299819.998303.2125
9836.671299.85159846.766296.23399850.854294.34799901.294266.65289909.546261.5414
9915.342258.51979929.635252.10299937.538247.33819951.534237.28559965.225230.3138
9973.255227.36039978.601226.3313   10001225.207210018.36225.932510037.84232.1468
10046.19233.505810088.77 238.04910105.72  238.2710121.37240.043810153.27247.5135
10169.73252.113310191.15255.864910203.74258.608210228.93262.003410250.97  267.27
#Mann= 3 , 0 , 0
9749.016    0.12       09749.016    0.12       010250.97    0.12       0
#XS Ineff= 2 , 0
       0                               0
Bank Sta=9749.016,10250.97
Exp/Cntr=0.3,0.1

Type RM Length L Ch R = 1 ,63489.33,478.604700,478.604700,478.604700
XS GIS Cut Line= 5
433439.941202774778887.072616129433363.599180478778997.646259595
 433295.02277745 779090.72372494 433293.90678479779092.383411774
433145.255185876779293.368916637
#Sta/Elev= 30
 9749.02341.70649758.654339.99079807.261314.16869855.869287.2356 9868.02281.3888
9880.922271.79989892.522265.54349904.943260.50969917.364250.25469931.603236.5359
9942.206228.95669954.627226.56799967.048215.2991 9982.18208.10599991.891208.7588
9999.041214.316210016.69 224.381 10032.8229.282710041.57236.239210049.61 245.005
10054.01248.436610066.44  254.5610103.76268.451610128.63279.165210141.07288.2868
10153.51295.768510178.39 317.45610190.82326.490810217.78336.407210250.98338.6165
#Mann= 3 , 0 , 0
 9749.02    0.12       0 9749.02    0.12       010250.98    0.12       0
#XS Ineff= 2 , 0
       0                               0
Bank Sta=9749.02,10250.98
Exp/Cntr=0.3,0.1

Type RM Length L Ch R = 1 ,63010.73,478.604800,478.604800,478.604800
XS GIS Cut Line= 6
433127.224767937778551.988076832433073.061856898778611.822965593
433025.469183162778668.128509792432991.701064125778711.578557459
432915.433179717 778816.08277636432810.926891564778941.318881506
#Sta/Elev= 30
9749.014316.71649780.053296.49769793.542282.2374 9807.03271.09839826.834259.3814
9873.163239.3946 9899.35230.00889904.211227.7159 9912.15223.10199924.814217.3037
9936.804212.32059950.144  207.819974.958203.60939987.238201.98529999.513 201.575
10011.74202.257510023.99204.5886   10039211.175710061.39222.106310088.54240.5579
10099.48245.245210104.15246.482410112.51 250.76210135.37267.7824 10164.6285.1393
10177.63292.117310203.68303.648610229.73318.569510244.62 325.79310250.98329.3617
#Mann= 3 , 0 , 0
9749.014    0.12       09749.014    0.12       010250.98    0.12       0
#XS Ineff= 2 , 0
       0                               0
Bank Sta=9749.014,10250.98
Exp/Cntr=0.3,0.1

Type RM Length L Ch R = 1 ,62532.12,478.604700,478.604700,478.604700
XS GIS Cut Line= 6
432853.997894649778252.179608856432755.288172172778325.227645813
432648.425706058778397.818254476432562.082264395778457.754782743
432497.882121899778507.298213161432449.367149641778548.695798642
#Sta/Elev= 30
9749.015 305.7269753.756303.44999770.567297.6106 9785.09291.7757 9797.53 285.319
 9809.97280.19529834.851266.16369847.292258.69019872.163245.78469884.252 241.784
9889.203239.74899896.342235.71949920.522225.22219932.611218.26939944.701 214.213
9956.791208.95969968.881 205.6539980.971201.001210017.34199.851610029.52199.9147
10041.69202.365210053.86206.472610083.74 214.76510102.56220.779610115.05  225.05
10190.99260.352610204.14 264.90910229.88272.600910243.57273.831210250.98276.4819
#Mann= 3 , 0 , 0
9749.015    0.12       09749.015    0.12       010250.98    0.12       0
#XS Ineff= 2 , 0
       0                               0
Bank Sta=9749.015,10250.98
Exp/Cntr=0.3,0.1

Type RM Length L Ch R = 1 ,62053.52,478.604800,478.604800,478.604800
XS GIS Cut Line= 6
432523.562861607777846.735007527432429.533314748777948.436869073
432311.717745661778060.347546826 432279.14513491778093.555882831
432231.649713593778149.917857968432185.008900005778215.764631345
#Sta/Elev= 30
9749.031247.23159776.375252.98489801.145263.93169814.764 264.2459835.296271.5318
9855.621 273.6139864.757272.3183 9869.24270.92929897.042250.94519925.997233.2855
9935.296224.08689949.125206.01489954.952201.37939962.954197.7382 9969.43196.5754
9983.908196.537310004.39197.179410027.61200.484210056.55202.517110088.19207.3272
10098.44210.051810102.99210.6539 10124.6210.370510134.02212.930210150.75219.0117
10165.06228.854610176.49235.724310199.06246.191510216.36255.749510250.95272.1541
#Mann= 3 , 0 , 0
9749.031    0.12       09749.031    0.12       010250.95    0.12       0
#XS Ineff= 2 , 0
       0                               0
Bank Sta=9749.031,10250.95
Exp/Cntr=0.3,0.1

Type RM Length L Ch R = 1 ,61574.92,386.282300,386.282300,386.282300
XS GIS Cut Line= 6
431939.338855873 777624.23684261431927.287830426 777723.16586748
431913.081170113777872.824792493431912.875534855 777874.81419294
431910.304239866777902.374082432431898.570923526778124.372793771
#Sta/Elev= 30
9749.008268.23159769.925261.02029779.999258.17569800.146254.40249820.294248.4036
9840.442240.50259850.511237.14449860.556232.56239880.646225.13699900.735215.3784
9920.825207.7326 9930.87205.38439940.915202.2185 9950.96 196.8869961.005193.2189
9981.095 193.54110001.19193.033410021.27194.353410041.32201.131410061.35203.1966
10081.38217.063310091.39 226.14310101.41233.205110111.42241.427210121.43246.3217
10141.46258.195410151.48263.4231 10171.5 266.36810221.57275.824210250.99283.2657
#Mann= 3 , 0 , 0
9749.008    0.12       09749.008    0.12       010250.99    0.12       0
#XS Ineff= 2 , 0
       0                               0
Bank Sta=9749.008,10250.99
Exp/Cntr=0.3,0.1