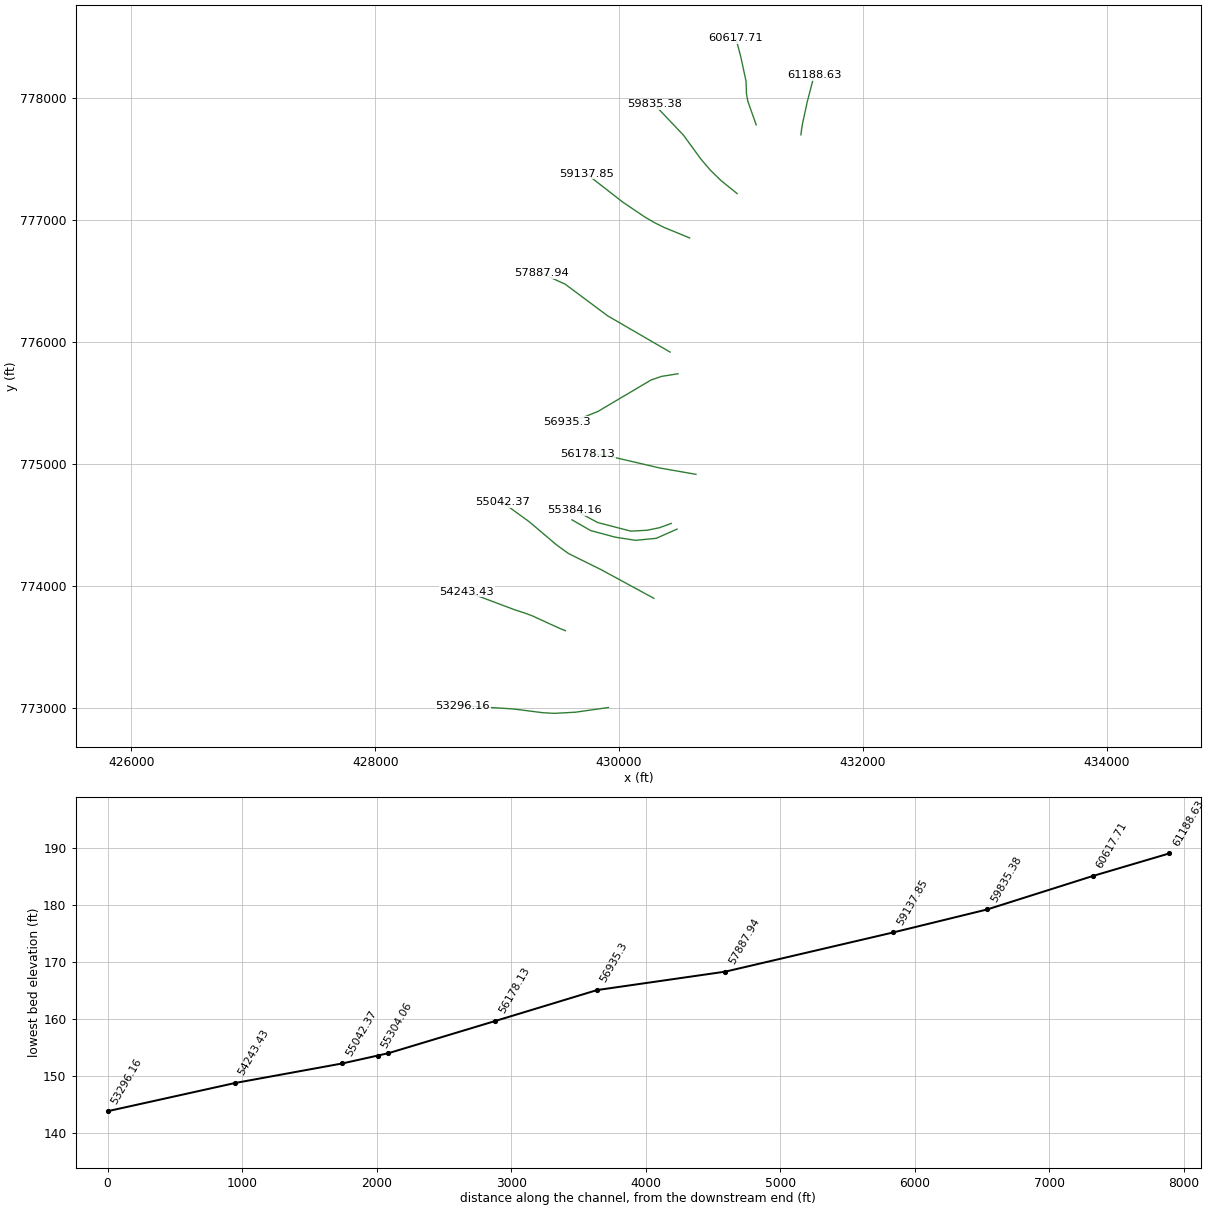
HEC-RAS study 2953_ras.prj: 2953

--- 2953_ras.g01 (geometry) --- (continued)

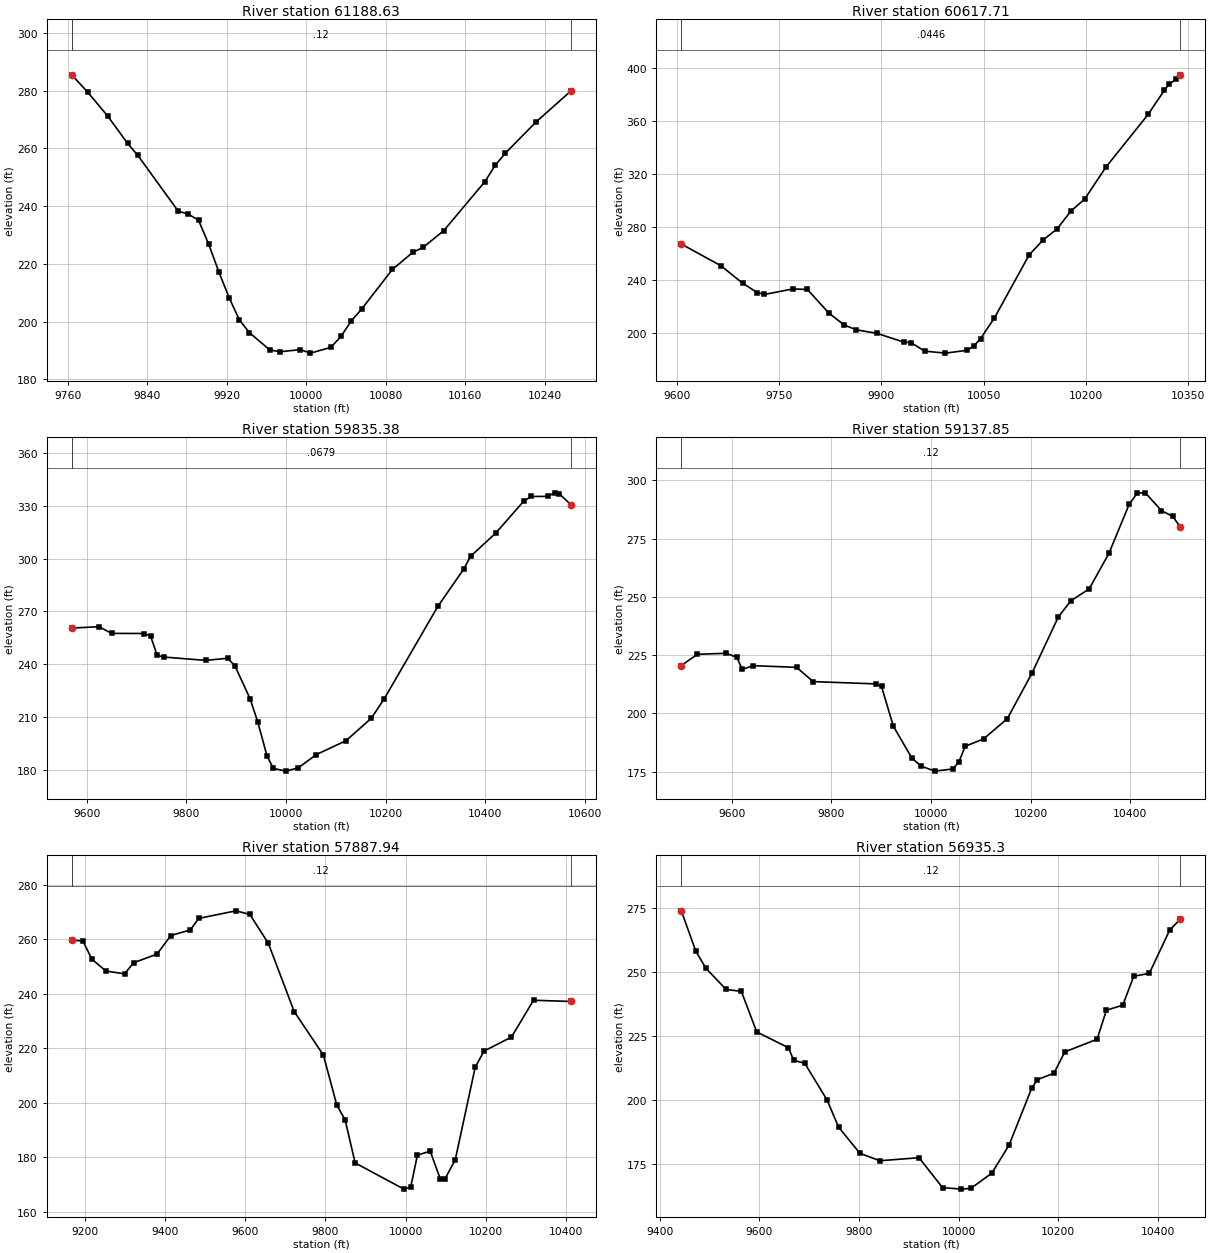
Type RM Length L Ch R = 1 ,61188.63,570.927200,570.927200,570.927200
XS GIS Cut Line= 6
431491.751672369777699.122542467431497.162106658777743.952640536
431505.698537995777794.169221749431538.421632352777944.535575921
431542.107090559777963.362473347431600.835197771778188.624915978
#Sta/Elev= 30
9763.979285.53019779.972279.59349800.117271.2785 9820.34261.75189830.484257.6246
9871.156238.2763 9881.39237.21569891.624 235.1149901.858226.75479912.092217.1495
9922.326208.3153 9932.56200.61659942.794196.14019963.262190.13349973.496189.5138
9993.964190.2457 10004.2189.038210024.62191.033710034.83194.803910045.17200.1943
 10055.5204.251810086.51218.035910107.17224.022310117.51225.703110138.18231.4994
10179.51 248.46410189.85254.109610200.18258.381810231.19269.239810265.93279.8958
#Mann= 3 , 0 , 0
9763.979    0.12       09763.979    0.12       010265.93    0.12       0
#XS Ineff= 2 , 0
       0                               0
Bank Sta=9763.979,10265.93
Exp/Cntr=0.3,0.1

Type RM Length L Ch R = 1 ,60617.71,782.326500,782.326500,782.326500
XS GIS Cut Line= 6
431124.979555517777780.864159793431056.083122969777975.436252475
431045.264475584778033.393739596431041.882646382778137.542912841
430998.542530268778339.216185555430958.585743129778490.621082231
#Sta/Elev= 30
9606.387267.30249664.351250.98549696.472237.7793 9717.68 230.7659728.269229.3006
9770.625233.48799791.545233.04599822.685 215.4019845.187206.35899863.418202.6117
9893.499199.99759933.502193.25489943.503 193.0159963.557186.55979994.167 185.052
10025.23187.134210035.49190.135410045.68196.033710066.07211.619610117.04259.1486
10137.43270.351710157.82 278.64210178.21292.068410198.76 301.40310229.65325.3151
10291.72365.118710315.51383.302510322.89388.213310333.28391.588210339.12394.9327
#Mann= 3 , 0 , 0
9606.387  0.0446       09606.387  0.0446       010339.12  0.0446       0
#XS Ineff= 2 , 0
       0                               0
Bank Sta=9606.387,10339.12
Exp/Cntr=0.3,0.1

Type RM Length L Ch R = 1 ,59835.38,697.530700,697.530700,697.530700
XS GIS Cut Line= 6
430968.411637586777217.137912186430836.137078982777323.987496408
430746.817797203777411.457664271430670.419589493777501.291630693
430528.801952502777695.633658667430289.066048119777947.958408915
#Sta/Elev= 30
9569.652260.44849624.591261.26829649.902257.46399714.904257.3842 9728.07256.0024
9741.295244.96599754.967244.00689838.806242.11469882.886243.32859897.676238.9097
9927.824220.33559943.632206.85489961.801 187.8069974.657 180.7679999.743179.1967
10024.54181.058910060.62188.561310120.68196.539510171.49209.325610197.37220.4027
10304.66272.743210357.04294.147110370.66301.320110420.84314.406810477.75332.7643
10491.98335.246510525.22335.294310539.28337.316710548.89336.711310571.56330.6155
#Mann= 3 , 0 , 0
9569.652  0.0679       09569.652  0.0679       010571.56  0.0679       0
#XS Ineff= 2 , 0
       0                               0
Bank Sta=9569.652,10571.56
Exp/Cntr=0.3,0.1

Type RM Length L Ch R = 1 ,59137.85,1249.910400,1249.910400,1249.910400
XS GIS Cut Line= 6
430578.733923466 776853.21408573430368.496652987776939.647426674
430291.206105452776978.289441972430212.817000169777023.804842664
430028.966188475777147.978977975429732.602762076777378.740477557
#Sta/Elev= 30
9499.038220.5113 9531.17225.34059589.045225.78819610.544  224.039621.293218.8227
9642.893 220.4789730.295219.73029763.835213.61219889.355212.63859900.918211.5267
9924.597194.47439961.303180.94799979.852177.3392 10007.8  175.1610044.27176.0778
10056.55179.282510068.83185.833610105.67188.976110153.45197.684610202.96217.2515
10256.06241.4992 10281.2248.353210317.78253.437110357.61268.800910398.32289.9119
10414.42 294.54310430.53294.703310462.75287.055310485.17284.609810500.99280.0261
#Mann= 3 , 0 , 0
9499.038    0.12       09499.038    0.12       010500.99    0.12       0
#XS Ineff= 2 , 0
       0                               0
Bank Sta=9499.038,10500.99
Exp/Cntr=0.3,0.1

Type RM Length L Ch R = 1 ,57887.94,952.638200,952.638200,952.638200
XS GIS Cut Line= 4
430419.031777084775916.447871611429906.878999323776213.756899387
429557.486638188776474.173566043429360.438027084776563.583288282
#Sta/Elev= 30
9167.642259.5761 9195.43259.35119218.556252.59289253.244248.27819299.495247.2723
9322.621251.35879380.435254.48919415.124261.32379463.535263.37079484.501267.5976
9577.003270.38099611.692269.10659657.943258.48829722.475233.43529795.383217.4211
 9828.85199.02529849.484193.67799874.428177.87129996.184168.262810012.92168.9783
10029.65180.696510061.51  182.2310086.45172.114410098.93 172.15510123.87178.9314
10173.76  212.98 10195.6218.905110264.22224.059410319.13237.569310411.99237.1284
#Mann= 3 , 0 , 0
9167.642    0.12       09167.642    0.12       010411.99    0.12       0
#XS Ineff= 2 , 0
       0                               0
Bank Sta=9167.642,10411.99
Exp/Cntr=0.3,0.1

Type RM Length L Ch R = 1 , 56935.3,757.165700,757.165700,757.165700
XS GIS Cut Line= 6
430483.951435757775738.938389143430348.697629409 775717.23205546
 430263.35950595775688.151758497429827.896762912 775430.47302082
 429705.51963458 775380.61921829429573.889815482775347.188068303
#Sta/Elev= 30
9443.156273.75769472.306257.96449492.444251.32539533.061243.04189563.627242.2844
9594.478226.45029658.034220.29329668.711215.3702 9690.83214.19899735.765 199.842
 9758.72189.2778 9801.52 179.0439841.648176.11699920.211177.30389967.496165.6232
10005.44165.028910024.41165.337110066.27171.244110100.91182.172510146.44204.4791
10157.69207.809410191.02210.300210212.89218.650210277.74223.597310296.38234.9333
10329.24236.900810351.33248.199310382.54249.325410423.44266.237510445.03270.5599
#Mann= 3 , 0 , 0
9443.156    0.12       09443.156    0.12       010445.03    0.12       0
#XS Ineff= 2 , 0
       0                               0
Bank Sta=9443.156,10445.03
Exp/Cntr=0.3,0.1

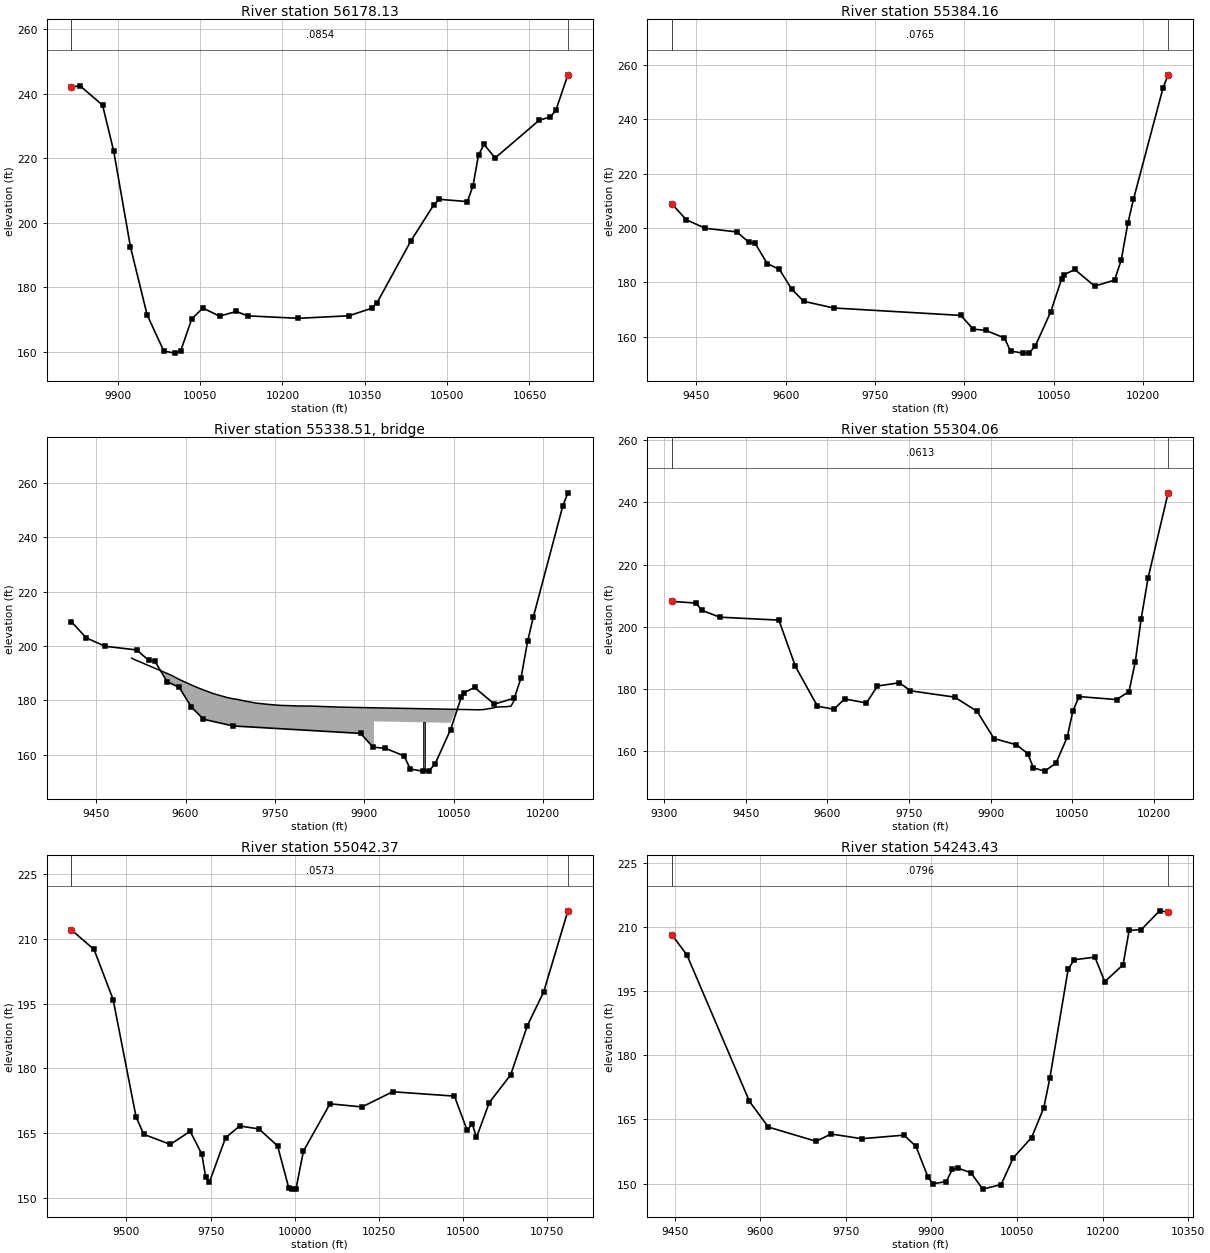
Type RM Length L Ch R = 1 ,56178.13,793.973500,793.973500,793.973500
XS GIS Cut Line= 5
430630.751394905774913.716587526430333.170054138774965.994390637
 429916.47702685775063.087911561429855.963457882775071.111343011
429743.158271171775082.679000172
#Sta/Elev= 30
9815.553242.08099831.545242.32399872.158236.39089892.464222.17069922.923192.5554
9953.383171.42869983.842160.205110004.15159.5937 10014.3160.148110034.61 170.166
10054.91173.555710085.37171.038310115.83172.504710136.35171.138110228.76170.3749
10321.17171.166610362.24 173.47210372.51175.266210434.12194.404210475.19205.4087
10485.46207.2415 10536.8206.527110547.04211.370910557.12220.946310567.21224.2417
10587.39220.040810667.87231.739210687.98232.744210698.03234.778710719.99245.7879
#Mann= 3 , 0 , 0
9815.553  0.0854       09815.553  0.0854       010719.99  0.0854       0
#XS Ineff= 2 , 0
       0                               0
Bank Sta=9815.553,10719.99
Exp/Cntr=0.3,0.1

Type RM Length L Ch R = 1 ,55384.16,80.097900,80.097900,80.097900
XS GIS Cut Line= 6
430428.009020293774511.005134619430331.246220678774475.665677384
430228.815665066774454.832344055430096.003165066774447.887899607
429825.050171077774518.185424224429637.987463504774618.053052157
#Sta/Elev= 30
9408.571208.91259433.067203.02489465.005199.8872 9517.96198.54959538.369194.6903
9548.574194.35349568.983186.90149589.393184.75069609.802177.53349629.988173.0308
9680.137170.55919893.831167.82129914.698162.76629935.566162.32039966.867159.5389
9977.301154.70059998.168153.9355 10008.6153.986710019.04156.653310044.94169.2367
10062.86 181.14810067.71182.853710085.12184.719410118.52178.602810151.91180.8192
10163.04188.145310174.17201.652710183.62210.525510233.42251.652810241.83256.3788
#Mann= 3 , 0 , 0
9408.571  0.0765       09408.571  0.0765       010241.83  0.0765       0
#XS Ineff= 2 , 0
       09872.461                       0
Bank Sta=9408.571,10241.83
Exp/Cntr=0.3,0.1

Type RM Length L Ch R = 3 ,55338.51,,,
BEGIN DESCRIPTION:
END DESCRIPTION:
Bridge Culvert--1,0,-1,-1, 0
Deck Dist Width WeirC Skew NumUp NumDn MinLoCord MaxHiCord MaxSubmerge Is_Ogee
22.168400,35.761100,2.6,0, 29, 29, , , 0.95, 0, 0,0,,
 9509.54 9515.74 9576.73 9586.90 9597.06 9617.39 9627.56 9647.89 9668.07 9678.08
 9688.09 9698.10 9718.12 9738.18 9758.32 9788.52 9808.66 9857.25 9916.34 9916.34
10083.6610083.6610089.6610100.0710114.2610122.0010137.9910146.3110153.82
  195.51  194.87  189.18  187.95  186.92  184.93  184.03  182.39  181.13  180.64
  180.30  179.80  178.99  178.52  178.15  177.92  177.89  177.51  177.25  177.25
  176.55  176.55  176.51  176.59  177.10  177.51  177.65  177.83  180.85
 -804.49 -805.13 -810.82 -812.05 -813.08 -815.07 -815.97 -817.61 -818.87 -819.36
 -819.70 -820.20 -821.01 -821.48 -821.85 -822.08 -822.11 -822.49 -822.75  172.25
  171.55 -823.45 -823.49 -823.41 -822.90 -822.49 -822.35 -822.17 -819.15
 9509.54 9515.74 9576.73 9586.90 9597.06 9617.39 9627.56 9647.89 9668.07 9678.08
 9688.09 9698.10 9718.12 9738.18 9758.32 9788.52 9808.66 9857.25 9916.34 9916.34
10083.6610083.6610089.6610100.0710114.2610122.0010137.9910146.3110153.82
  195.51  194.87  189.18  187.95  186.92  184.93  184.03  182.39  181.13  180.64
  180.30  179.80  178.99  178.52  178.15  177.92  177.89  177.51  177.25  177.25
  176.55  176.55  176.51  176.59  177.10  177.51  177.65  177.83  180.85
 -804.49 -805.13 -810.82 -812.05 -813.08 -815.07 -815.97 -817.61 -818.87 -819.36
 -819.70 -820.20 -821.01 -821.48 -821.85 -822.08 -822.11 -822.49 -822.75  172.25
  171.55 -823.45 -823.49 -823.41 -822.90 -822.49 -822.35 -822.17 -819.15
Pier Skew, UpSta & Num, DnSta & Num=  ,10000.00, 2 ,10000.00, 2 , 0 , 0 , 0 ,,
    4.00    4.00
 -823.12  176.88
    4.00    4.00
 -823.12  176.88
BR Coef=-1 , 0 , 0 ,, 0 ,,,0.8,0,1,0,
WSPro=,,,, 1 ,,,, 0 ,,,, 0 ,,,,-1 ,-1 ,-1 , 0 , 0 , 0 , 0 , 0
BC Design=,, 0 ,, 0 ,,,,,,

Type RM Length L Ch R = 1 ,55304.06,261.689500,261.689500,261.689500
XS GIS Cut Line= 6
430475.780542588774464.484944367430305.204553962774388.860121816
430135.065665066774372.367066264429967.751159012774398.355063856
429766.261478364 774452.70541288429613.459111959774540.754356101
#Sta/Elev= 30
9314.109208.17069358.718207.61349369.656 205.2689402.473203.0791 9511.05202.1295
9541.486187.20499581.878174.43959611.915173.4346 9631.94176.75099671.991175.4543
9692.203180.91999732.628181.96039752.847179.37059833.906177.34659875.173172.7749
9906.245164.00569947.675161.9959 9968.39159.14759978.747154.56269999.462153.5142
10020.18156.067710040.89164.449410051.39172.927210062.83177.5067 10131.5 176.553
10154.39179.122310166.04188.722810176.68202.427310189.43 215.66310226.33243.1127
#Mann= 3 , 0 , 0
9314.109  0.0613       09314.109  0.0613       010226.33  0.0613       0
#XS Ineff= 2 , 0
       09847.048                       0
Bank Sta=9314.109,10226.33
Exp/Cntr=0.3,0.1

Type RM Length L Ch R = 1 ,55042.37,798.948000,798.948000,798.948000
XS GIS Cut Line= 6
   430285.242028773896.851171458429849.083822832 774133.54443714
 429584.65336075 774264.26762031429486.991450465774335.015679804
429262.748241287774525.001155548 429045.49498685774682.686123347
#Sta/Elev= 30
9336.654211.98699403.724207.48199460.351195.92689528.305168.89019551.174164.7932
9630.435162.47269689.153165.49759723.648160.26399735.145154.99029746.536153.7681
9794.284163.99849836.266166.71829893.475 166.0459948.833162.12939981.752152.5141
9992.725152.1384 10003.7152.281310025.72160.922410104.56171.841410199.65171.1175
10290.76174.625110474.25173.620510511.79165.770810527.26167.193810539.78 164.078
 10577.7172.119710641.32178.530110690.93189.915710739.45197.697210811.29 216.411
#Mann= 3 , 0 , 0
9336.654  0.0573       09336.654  0.0573       010811.29  0.0573       0
#XS Ineff= 2 , 0
       0  9751.1        10112.68       0
Bank Sta=9336.654,10811.29
Exp/Cntr=0.3,0.1

Type RM Length L Ch R = 1 ,54243.43,947.264200,947.264200,947.264200
XS GIS Cut Line= 6
429559.518978499773630.734018098429507.589611202773652.180869222
429290.634101331 773751.69798246429233.029044092773773.605765641
429146.757130533773801.437702999 428751.04684974773950.098783295
#Sta/Elev= 30
9444.896208.17349471.424203.4377 9581.14 169.1999614.228163.19529697.931159.8706
9724.117161.57459777.908160.4709 9851.88161.30939872.895158.68019893.941151.5092
9902.193149.93139925.988150.46179936.671153.31529947.353153.54529968.718152.5694
9990.083148.693510022.13149.758510043.49156.017210075.54160.748310096.91167.7059
10107.59 174.69510139.64200.112510150.32 202.30110186.54202.898810203.73197.1695
10235.78201.114910246.46209.138710267.83209.349210299.87213.728610314.78213.4681
#Mann= 3 , 0 , 0
9444.896  0.0796       09444.896  0.0796       010314.78  0.0796       0
#XS Ineff= 2 , 0
       09699.277                       0
Bank Sta=9444.896,10314.78
Exp/Cntr=0.3,0.1

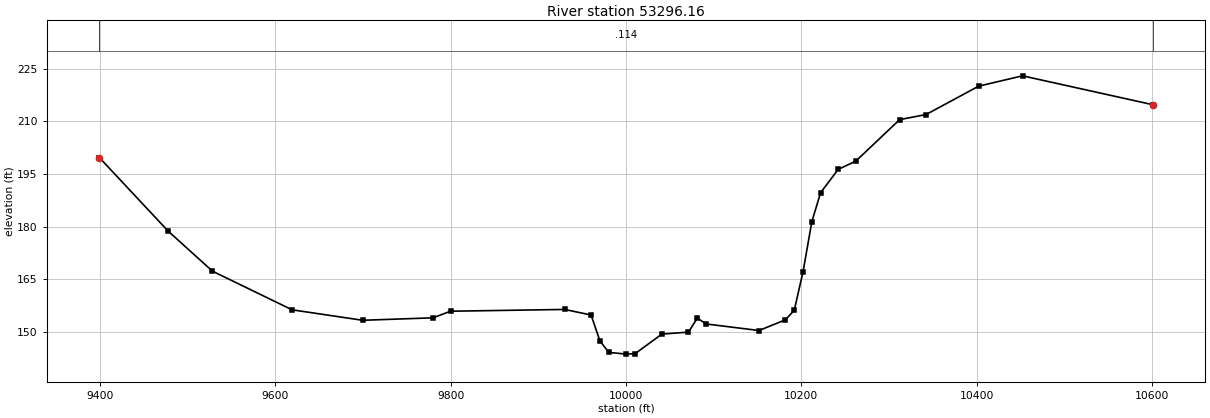
Type RM Length L Ch R = 1 ,53296.16,947.264200,947.264200,947.264200
XS GIS Cut Line= 6
429912.648225865 773000.69459324429642.409531515  772962.3472867
429468.316976122772952.677809806429369.624186696772958.729951649
429131.455284533772989.051853219428716.824289919773015.372771491
#Sta/Elev= 30
9399.045199.6753 9477.57178.73899528.134167.33819618.983156.34539699.506153.3678
9779.757 154.069 9799.76155.94659929.926156.45219960.115154.87329970.206147.4989
9980.298144.229610000.49143.737110010.59143.910210040.91149.445610071.23149.9905
10081.34153.991510091.42 152.31910151.76150.457710181.92153.517610191.96156.2335
10201.99167.211110212.01181.435610222.04189.693310242.09196.310210262.14198.6495
10312.21210.467810342.25211.906210402.33219.9862 10452.4222.930110600.98214.7195
#Mann= 3 , 0 , 0
9399.045   0.114       09399.045   0.114       010600.98   0.114       0
#XS Ineff= 2 , 0
       09709.065         10343.4       0
Bank Sta=9399.045,10600.98
Exp/Cntr=0.3,0.1