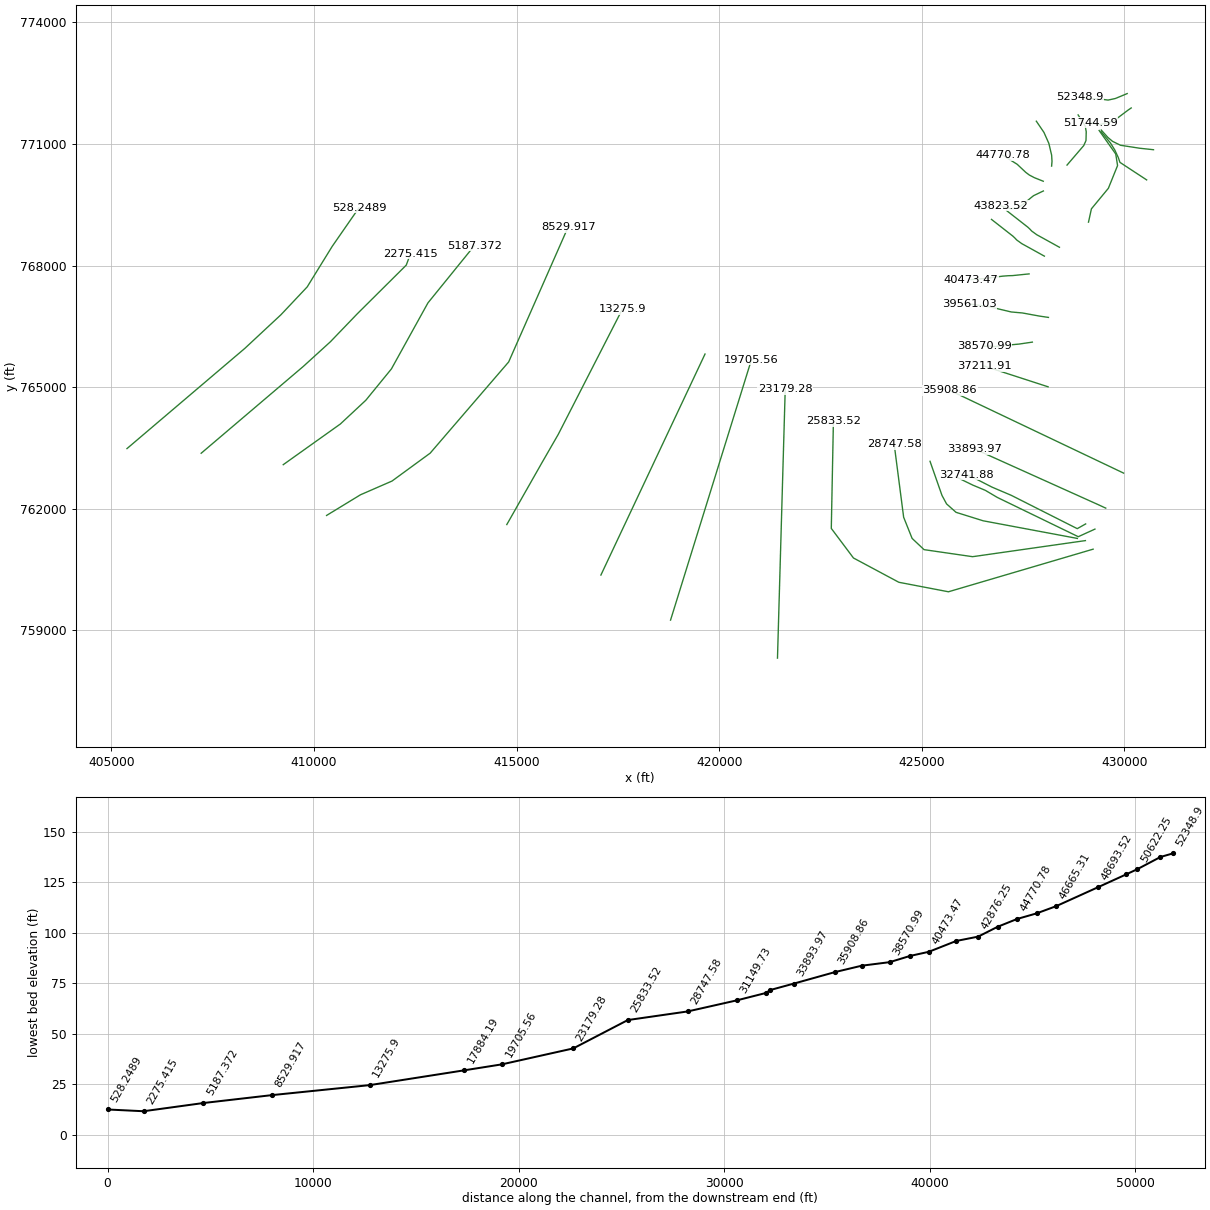
HEC-RAS study 2953_ras.prj: 2953

--- 2953_ras.g01 (geometry) --- (continued)

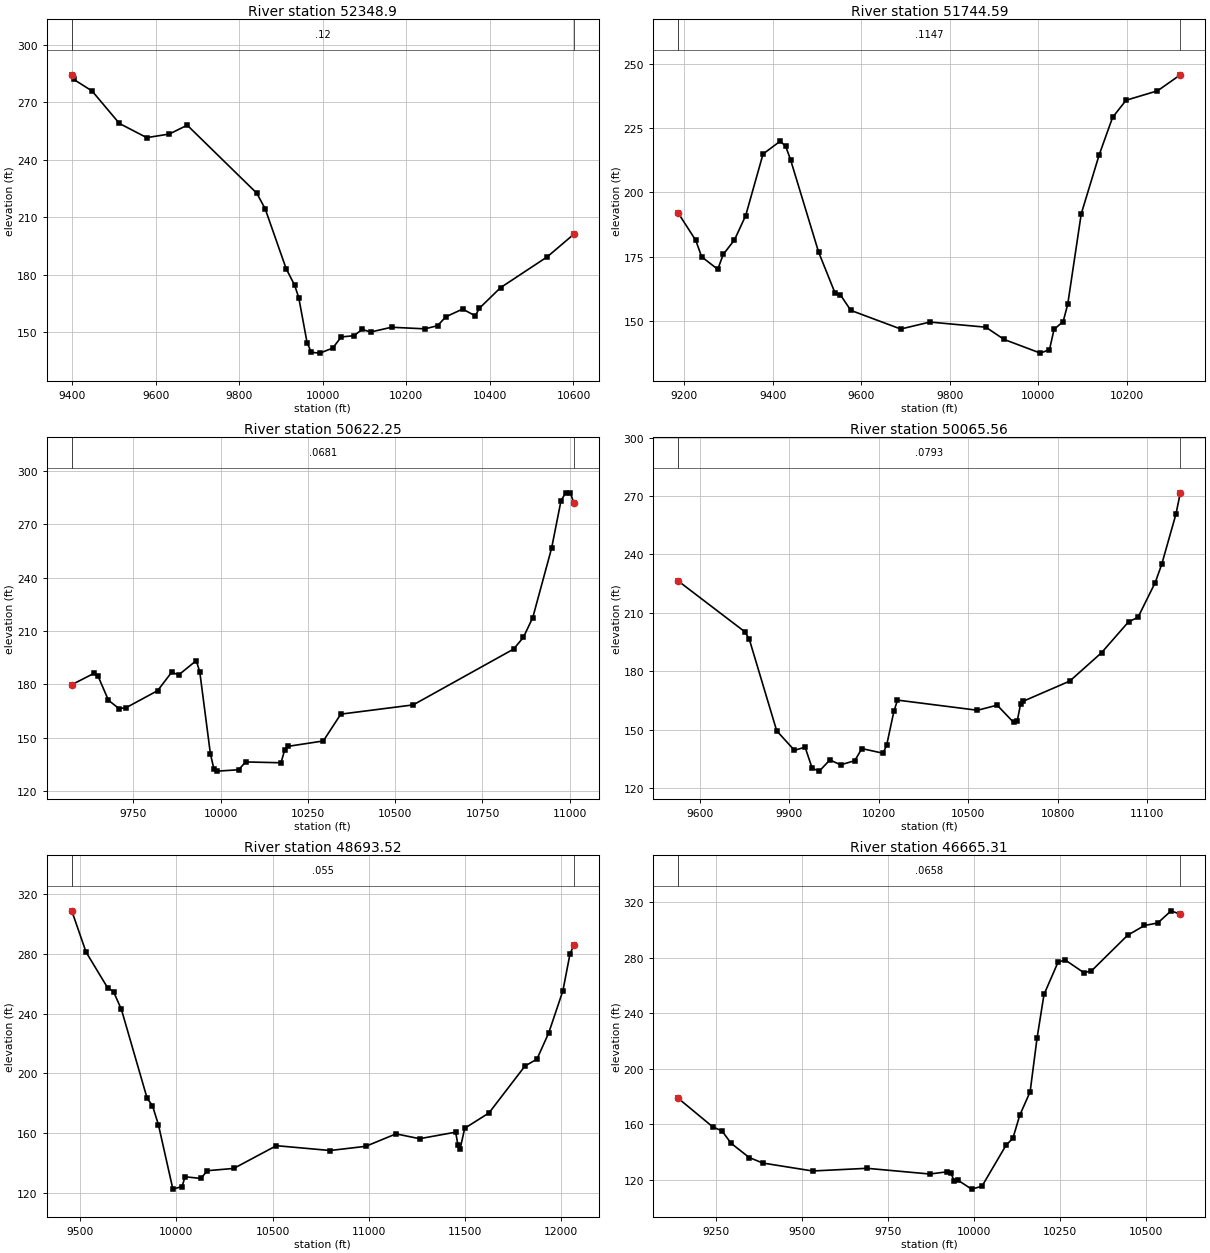
Type RM Length L Ch R = 1 , 52348.9,604.307900,604.307900,604.307900
XS GIS Cut Line= 6
430069.437276679772241.723357416429777.068660881772120.476364636
429599.664319324772082.193530235429426.600637678772103.250465886
429117.928050175772121.119269701428903.236753049 772162.83290327
#Sta/Elev= 30
9399.091284.28549403.935281.86739447.603275.87099513.105258.92589578.608251.5303
9632.662 253.4249675.479258.01869841.829   222.69862.119214.39129912.327183.1585
 9932.34174.7038 9942.36168.1646  9962.4144.59549972.575139.60249992.961139.1797
10023.76141.814510044.15147.621710074.37148.256310094.38151.5402 10114.4150.1788
10164.45152.671910244.52151.840510274.57153.477510294.64158.134210334.78 162.163
10364.88158.614910374.92 162.60610425.46173.313910537.19189.376410600.91201.1797
#Mann= 3 , 0 , 0
9399.091    0.12       09399.091    0.12       010600.91    0.12       0
#XS Ineff= 2 , 0
       0                10351.85       0
Bank Sta=9399.091,10600.91
Exp/Cntr=0.3,0.1

Type RM Length L Ch R = 1 ,51744.59,1122.341600,1122.341600,1122.341600
XS GIS Cut Line= 6
430168.475838602771887.475762948430091.115556538771834.164379075
429753.090171248771580.012549505429622.881837904771532.269493937
429397.187393486771480.186160594429154.131837964771519.248660594
#Sta/Elev= 30
9186.866191.94519226.475181.30429239.666174.92599276.099170.05519288.545175.8773
9313.819181.49629339.093190.94569378.347214.94549417.162219.93599429.527 217.903
9440.411212.74829503.717176.77979540.812160.83569553.177160.05429576.426154.0655
9689.192146.80299755.139149.5115 9881.41147.51049922.385142.7561 10004.5137.4135
10025.07138.792110035.35146.642810055.92 149.725 10066.2156.393410096.71191.6345
10137.22214.609110167.61 229.24310197.99235.876510268.89239.538510320.41245.7729
#Mann= 3 , 0 , 0
9186.866  0.1147       09186.866  0.1147       010320.41  0.1147       0
#XS Ineff= 2 , 0
       0                               0
Bank Sta=9186.866,10320.41
Exp/Cntr=0.3,0.1

Type RM Length L Ch R = 1 ,50622.25,556.691300,556.691300,556.691300
XS GIS Cut Line= 6
430719.345854193770857.228861824 430375.08068642770894.508132741
429904.999893486770967.165327281 429707.08322683 771064.38754949
429595.972115695 771158.13754949429429.305449039771342.165327266
#Sta/Elev= 30
9574.102179.88319638.824186.36389648.882184.88599679.057171.17199709.233166.4855
 9729.35166.95189819.876176.5414 9860.11186.87719880.227185.36199930.554193.3969
9940.647186.96799970.927141.18699981.021132.61439991.114131.3971 10051.8132.1635
10072.05136.555110173.22136.0875 10183.3143.052810193.38145.3042 10294.2148.3182
10344.38163.369210551.51168.547510839.17199.876810866.94206.406110893.92217.5283
10947.89256.511610974.87283.208710988.36287.518211001.85287.383911011.52281.7329
#Mann= 3 , 0 , 0
9574.102  0.0681       09574.102  0.0681       011011.52  0.0681       0
#XS Ineff= 2 , 0
       0                               0
Bank Sta=9574.102,11011.52
Exp/Cntr=0.3,0.1

Type RM Length L Ch R = 1 ,50065.56,1372.039800,1372.039800,1372.039800
XS GIS Cut Line= 6
430549.921003163770112.829105422  429890.8237966770545.075514928
429849.444337904770665.081993952429762.638782352770852.581993952
429654.999893486771026.193105042  429425.8332268771300.498660609
#Sta/Elev= 30
9526.849226.33179749.196200.40689764.885196.63469857.199149.44759916.705139.4304
9952.409141.06519976.211130.210810000.01128.758310035.72134.523310071.42131.9813
10119.03134.108510142.89140.326310214.54137.926310226.48142.396410250.36159.4471
10262.31165.2122 10530.7160.001610596.82162.6149 10652.1153.735310663.87154.3389
10675.63163.399310682.73164.533810840.36174.977510947.08189.561811037.43205.3854
11069.26207.714111127.02225.558511148.86234.930911196.61260.7196 11211.2271.6059
#Mann= 3 , 0 , 0
9526.849  0.0793       09526.849  0.0793       0 11211.2  0.0793       0
#XS Ineff= 2 , 0
       0                               0
Bank Sta=9526.849,11211.2
Exp/Cntr=0.3,0.1

Type RM Length L Ch R = 1 ,48693.52,2028.204600,2028.204600,2028.204600
XS GIS Cut Line= 6
429114.593973875769070.901733264429186.863303214769399.705991462
429605.640989184769906.559498563  429832.0832268770467.165327266
429786.944337904 770751.88754949429377.222115695771331.748660609
#Sta/Elev= 30
9456.107308.9164 9530.25281.27989641.829257.4506 9672.98254.74349714.072242.7913
9847.802183.21749875.226178.40539906.442165.4988 9981.48122.396310029.13124.1285
 10044.8130.6707 10127.2  129.5510160.08134.747710297.58136.264210519.25151.5156
10798.41148.279310983.54151.086111140.97159.433211263.39 156.18711450.78160.5855
11462.49151.9254 11474.2149.475711497.62163.166311623.86173.453911810.85204.8951
11873.13209.526311934.27227.097512007.64255.215912044.32279.6802 12064.8286.1536
#Mann= 3 , 0 , 0
9456.107   0.055       09456.107   0.055       0 12064.8   0.055       0
#XS Ineff= 2 , 0
       0                               0
Bank Sta=9456.107,12064.8
Exp/Cntr=0.3,0.1

Type RM Length L Ch R = 1 ,46665.31,947.264200,947.264200,947.264200
XS GIS Cut Line= 6
428584.687393486770478.450049505428996.415947795770958.598588377
429052.822083771771083.367449418429058.574768543771298.350901991
429035.539417684771438.957363203428858.720372885771715.597058848
#Sta/Elev= 30
9141.294178.55349242.134 157.851 9268.48155.05259294.827146.16299347.519135.8578
9387.038131.87929531.943126.1493 9690.02128.07539872.482123.96079923.908125.5832
9934.017124.48779944.127118.81749954.157119.52889994.207113.063610024.21115.1299
10094.21144.688910114.21 149.76910134.23166.3942 10164.3 183.28110184.45222.0089
10204.63253.430210245.52276.750810266.35278.290410319.93 269.252   10342270.2762
10447.39296.064210496.75303.187110535.25304.975110574.18313.7494 10600.9311.2623
#Mann= 3 , 0 , 0
9141.294  0.0658       09141.294  0.0658       0 10600.9  0.0658       0
#XS Ineff= 2 , 0
       0                               0
Bank Sta=9141.294,10600.9
Exp/Cntr=0.3,0.1

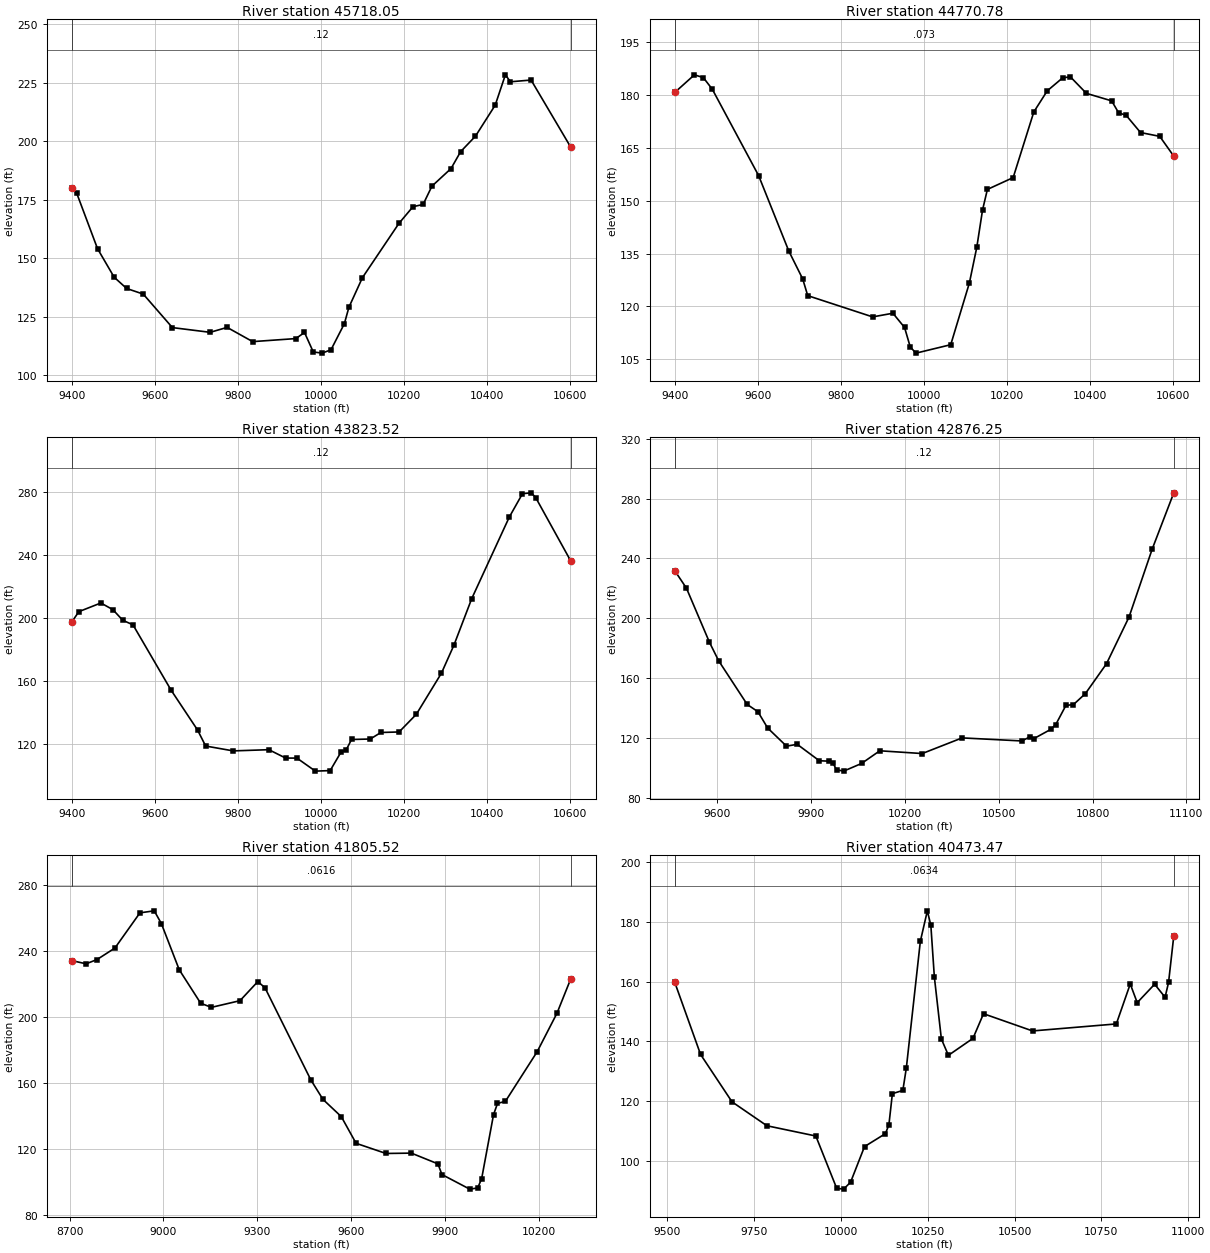
Type RM Length L Ch R = 1 ,45718.05,947.264200,947.264200,947.264200
XS GIS Cut Line= 6
428204.455930186770452.964291426 428214.06986845770569.501453732
428205.169968319770722.206502058428136.488251061771013.236860471
  428015.7709968771283.955152415427827.213078634771561.178279985
#Sta/Elev= 30
9399.072180.06069411.178177.94339461.467 154.148 9501.54141.9548 9531.56 137.144
9571.571134.7474 9641.79 120.425 9732.74118.40649773.589120.51289835.114 114.432
9938.998115.73059959.932118.3356 9981.06110.019410002.35 109.51510023.79 110.957
10055.99122.112810066.84129.083410099.41141.754810187.42164.970410221.24 172.097
10245.58173.046510266.84180.874810312.85188.394310336.02195.6295 10371.7202.2311
10419.26215.495310443.71228.4471   10456 225.47410505.63 226.22210600.96197.5987
#Mann= 3 , 0 , 0
9399.072    0.12       09399.072    0.12       010600.96    0.12       0
#XS Ineff= 2 , 0
       0                               0
Bank Sta=9399.072,10600.96
Exp/Cntr=0.3,0.1

Type RM Length L Ch R = 1 ,44770.78,947.264200,947.264200,947.264200
XS GIS Cut Line= 6
427998.926328377770079.695491776427778.935176126 770168.07103363
 427657.09679184770231.696820593427568.988408791 770296.85136386
427354.355218707770498.443694604426995.673310164 770721.65568564
#Sta/Elev= 30
9399.102180.76479446.441185.77039467.994184.97569489.548181.67729601.116 157.154
9673.744135.74649707.241127.82799719.369123.0752 9875.67 117.0419924.516118.0801
9952.568114.03739966.325108.48989980.082106.753510063.77109.143210108.68126.6729
10126.59136.849110140.35147.379510152.03153.233110214.13156.591410263.83175.2266
10296.23181.230310333.33184.914310351.89185.203110390.49180.5091 10451.3178.3765
10468.11174.993210486.22174.272110520.87169.384410567.08168.303210600.96162.6813
#Mann= 3 , 0 , 0
9399.102   0.073       09399.102   0.073       010600.96   0.073       0
#XS Ineff= 2 , 0
       0                               0
Bank Sta=9399.102,10600.96
Exp/Cntr=0.3,0.1

Type RM Length L Ch R = 1 ,43823.52,947.264200,947.264200,947.264200
XS GIS Cut Line= 6
428001.391186596769840.001141398427758.534527411769723.721597743
427445.384751181 769469.86882637427345.498407415769414.874598144
427172.580624879769403.812109445426945.646104803769475.911366669
#Sta/Elev= 30
9399.087197.46769416.456204.19179469.492209.7042 9498.34 205.4979522.341198.7069
9546.848195.83349638.253  154.489702.348 129.0189721.835 118.8389788.206115.7453
9874.091116.5081 9914.49111.18959941.651111.17329986.078102.891210021.72103.2305
 10047.5114.825310060.39116.450210073.24122.991110118.29123.293510143.94 127.444
10187.68 127.76810229.24139.002810289.67165.131210319.71 182.88110362.51212.4089
10453.15264.319410484.82279.139510506.04279.684610516.65276.665910600.86236.5024
#Mann= 3 , 0 , 0
9399.087    0.12       09399.087    0.12       010600.86    0.12       0
#XS Ineff= 2 , 0
       0                               0
Bank Sta=9399.087,10600.86
Exp/Cntr=0.3,0.1

Type RM Length L Ch R = 1 ,42876.25,1070.739700,1070.739700,1070.739700
XS GIS Cut Line= 6
428397.768934773768451.302251443427838.741156952768760.330029219
427715.326470481768849.357665777427665.453025268768902.623620987
427619.255937533768945.418365568427092.213379191769357.552251473
#Sta/Elev= 30
9464.016231.85239501.459220.15919575.009 184.0579604.295171.74419695.704142.5476
9729.983137.69059761.038126.83779821.392114.70179855.671115.92339926.397104.9494
9958.507104.66379969.933103.39789981.35998.9511410004.2198.0244710061.34103.1307
10119.72111.604110255.43109.761610383.06120.211410574.01118.1748 10599.4120.8499
 10612.1119.679710666.19125.865810682.42129.087310714.89141.889210739.04142.4482
10777.13149.747910844.76169.732310916.76200.888810990.86246.255311059.94283.8327
#Mann= 3 , 0 , 0
9464.016    0.12       09464.016    0.12       011059.94    0.12       0
#XS Ineff= 2 , 0
       0                               0
Bank Sta=9464.016,11059.94
Exp/Cntr=0.3,0.1

Type RM Length L Ch R = 1 ,41805.52,1332.040500,1332.040500,1332.040500
XS GIS Cut Line= 6
428026.241156995768232.552251443427467.213379174768541.580029219
427343.798692703768630.607665777 427293.92524749768683.873620987
427247.728159755768726.668365568426720.685601413769138.802251473
#Sta/Elev= 30
8706.592234.08028752.991232.12758787.994234.72128845.125241.66868925.108262.9441
8970.813264.16278993.665256.43429050.796228.51259119.354208.26999153.632205.7831
9245.042209.82369302.173 221.3949325.025217.61299471.381161.99119510.397150.1378
9568.921139.72859616.296123.57219711.927117.42849793.096117.63939878.123111.1375
9890.818104.70019979.67995.8638110005.0796.5549410017.76102.083410055.85140.8792
10068.54147.684510093.93148.981210195.48178.990710258.96202.315710302.52222.8926
#Mann= 3 , 0 , 0
8706.592  0.0616       08706.592  0.0616       010302.52  0.0616       0
#XS Ineff= 2 , 0
       0                               0
Bank Sta=8706.592,10302.52
Exp/Cntr=0.3,0.1

Type RM Length L Ch R = 1 ,40473.47,912.448600,912.448600,912.448600
XS GIS Cut Line= 6
427648.973737508767794.606553704427239.854825199767752.583700538
427142.739752442  767750.0521539426996.123211682767738.946853608
426595.218732148767685.320895448426219.992868006767653.971406668
#Sta/Elev= 30
9521.971159.81169596.334135.63479686.807119.76149787.333111.7383 9928.07108.3092
9988.11690.7880410008.1290.5082310028.1392.8346310068.23104.760910128.39 109.099
10138.42 112.06610148.45 122.50310178.56 123.58310188.63131.110210228.92173.5417
10249.08183.766610259.18178.898910269.29161.5757 10289.5140.810110309.71135.3474
10380.45141.029810410.77149.285310551.93143.517510793.07145.866210833.17159.2549
10853.23152.996910903.35159.173710933.43 154.80410943.46159.7792 10958.5175.3675
#Mann= 3 , 0 , 0
9521.971  0.0634       09521.971  0.0634       0 10958.5  0.0634       0
#XS Ineff= 2 , 0
       09868.948         10220.6       0
Bank Sta=9521.971,10958.5
Exp/Cntr=0.3,0.1

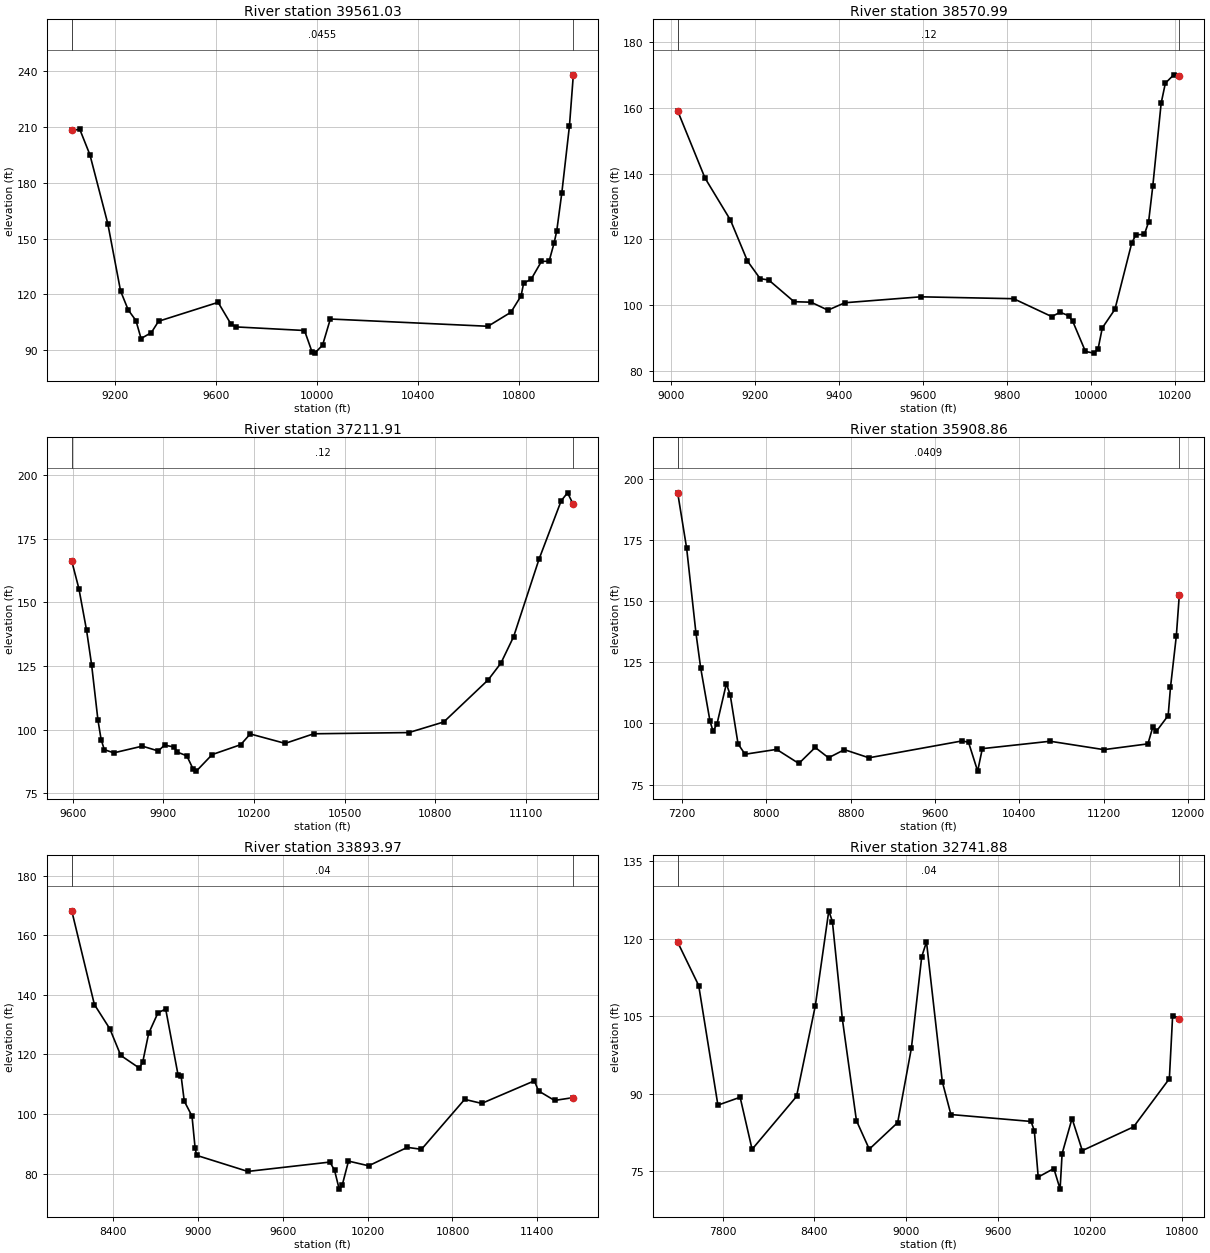
Type RM Length L Ch R = 1 ,39561.03,990.032200,990.032200,990.032200
XS GIS Cut Line= 6
428126.368558198766721.246159554427896.550716788766755.352378339
427485.679304421766830.746096164427208.012639642766855.819470152
426655.958957285766986.959448725426169.807070851767051.550998151
#Sta/Elev= 30
9027.839208.29949059.507208.89559099.888195.1279 9170.64158.11299221.259121.8948
 9251.63111.6795 9282.07106.00039302.38196.312459343.00399.48271 9371.83105.6171
9607.633115.77419658.341104.15369678.619102.56619949.901 100.6359980.53388.82908
9990.77988.4660210021.5292.7543410052.25106.8157 10676.8102.911610767.59110.4404
10807.94119.279210818.03126.074910848.29128.315610888.65137.821610918.91137.8791
10939.09147.908110949.17 154.16710969.35 174.71710999.61210.803811014.94238.1528
#Mann= 3 , 0 , 0
9027.839  0.0455       09027.839  0.0455       011014.94  0.0455       0
#XS Ineff= 2 , 0
       09863.461        10416.67       0
Bank Sta=9027.839,11014.94
Exp/Cntr=0.3,0.1

Type RM Length L Ch R = 1 ,38570.99,1359.087900,1359.087900,1359.087900
XS GIS Cut Line= 6
427729.209566236766112.022421822427401.950775653766064.038127109
427023.852625579766028.223864794426818.149280012766002.300728858
 426676.19939056766013.095600799426541.827415824766014.034952939
#Sta/Elev= 30
9015.829159.05649080.824 138.6669141.558125.85049182.045113.40089212.323108.0398
9232.508107.65359293.063101.03529333.433100.88679373.713 98.4664 9413.95100.7191
 9594.73102.52339816.036101.94629906.80796.511399926.88597.823819946.91396.78013
9956.91495.045219987.06985.9098410007.1585.3954910017.1986.6887510027.2293.06113
10057.3298.7229110097.39118.899510107.39121.4155 10127.4121.4957 10137.4125.2071
 10147.4136.0795 10167.4161.385310177.41167.495410197.41170.040310210.58169.7924
#Mann= 3 , 0 , 0
9015.829    0.12       09015.829    0.12       010210.58    0.12       0
#XS Ineff= 2 , 0
       09512.367        10096.69       0
Bank Sta=9015.829,10210.58
Exp/Cntr=0.3,0.1

Type RM Length L Ch R = 1 ,37211.91,1303.050900,1303.050900,1303.050900
XS GIS Cut Line= 2
428117.582587659765009.846657887426536.657823652765522.482807025
#Sta/Elev= 30
9596.139 166.2189619.879155.35169645.266138.98459661.929125.48249682.955103.7038
9693.46796.07105 9703.9892.088039735.518 90.82799830.131 93.46989882.69491.57098
9903.71993.854549935.25793.13008 9945.7791.129629977.30789.667939998.33384.45947
10008.8583.6430810061.4190.1493410156.0294.0432710187.5698.26222 10303.294.54706
10397.8198.3206710713.19 98.799910828.83102.9692   10976119.527611018.05126.0827
 11060.1136.454411144.21166.887111217.79189.907111238.82193.0456 11258.1188.4667
#Mann= 3 , 0 , 0
9596.139    0.12       09596.139    0.12       0 11258.1    0.12       0
#XS Ineff= 2 , 0
       0                10578.74       0
Bank Sta=9596.139,11258.1
Exp/Cntr=0.3,0.1

Type RM Length L Ch R = 1 ,35908.86,2014.888700,2014.888700,2014.888700
XS GIS Cut Line= 2
429981.583691239762880.978081465425689.917024583764922.644748136
#Sta/Elev= 30
  7162.5194.34867247.308171.7204  7335.9136.86037380.195122.76927468.787100.9164
7497.75296.83728 7535.2399.813887623.822116.26447660.697111.55177734.56191.60106
7801.00487.39191    810089.374268310.40583.61213 8465.4490.16652 8591.8185.93604
8742.28889.26333 8974.8485.931879860.75492.860719918.64792.2339810004.71  80.478
10049.0189.68031 10691.392.70297 11200.789.2686111617.9391.63437 11665.898.71932
11699.02 96.803911809.76103.213411831.91114.790611887.28135.830711915.06152.3396
#Mann= 3 , 0 , 0
  7162.5  0.0409       0  7162.5  0.0409       011915.06  0.0409       0
#XS Ineff= 2 , 0
       09155.427        10739.04       0
Bank Sta=7162.5,11915.06
Exp/Cntr=0.3,0.1

Type RM Length L Ch R = 1 ,33893.97,1152.083100,1152.083100,1152.083100
XS GIS Cut Line= 3
429540.558425833762017.360299603429359.180024607762100.879334157
426303.601842774763476.203893935
#Sta/Elev= 30
8104.862168.2663 8265.11136.78298374.927128.58278451.691119.67828583.286115.4237
8606.952117.36738649.084127.04618714.881133.97068769.713135.27958857.443113.1116
8879.376 112.6388901.308104.32598956.13999.275798978.07288.548368989.03886.09476
9350.92680.700379932.13883.843359965.03781.097479997.93674.7514510019.8776.15838
10063.7384.17444 10206.382.5903810480.4588.7832410580.4388.12914 10886.2104.9138
11006.83103.557211379.69111.1422 11408.8107.757711522.25104.553611655.38105.5099
#Mann= 3 , 0 , 0
8104.862    0.04       08104.862    0.04       011655.38    0.04       0
#XS Ineff= 2 , 0
       09283.014                       0
Bank Sta=8104.862,11655.38
Exp/Cntr=0.3,0.1

Type RM Length L Ch R = 1 ,32741.88,179.828900,179.828900,179.828900
XS GIS Cut Line= 6
429044.795844465761627.814114884428837.133918017761511.107971504
427210.952949047762332.109035298426731.786282361762536.275701955
426249.841837734762782.803479761426104.665134221762839.846872255
#Sta/Elev= 30
7506.192119.3503 7643.61 110.9647769.12387.813157914.32689.340637992.51279.26172
8282.91789.493178405.781107.04038493.943125.42668517.475123.34668582.529104.4826
8674.62284.814868758.51779.291288944.07184.436669033.88798.87128 9101.25116.5305
9132.491119.41879235.974 92.33879292.10985.995249816.02984.655769837.415 82.8439
9862.75373.893359964.88175.5443210005.8271.5562710018.9678.4229310083.9285.22609
10150.8979.0113610486.0283.6057710719.9592.9274710741.44105.158110784.78104.5133
#Mann= 3 , 0 , 0
7506.192    0.04       07506.192    0.04       010784.78    0.04       0
#XS Ineff= 2 , 0
       09720.344        10096.59       0
Bank Sta=7506.192,10784.78
Exp/Cntr=0.3,0.1

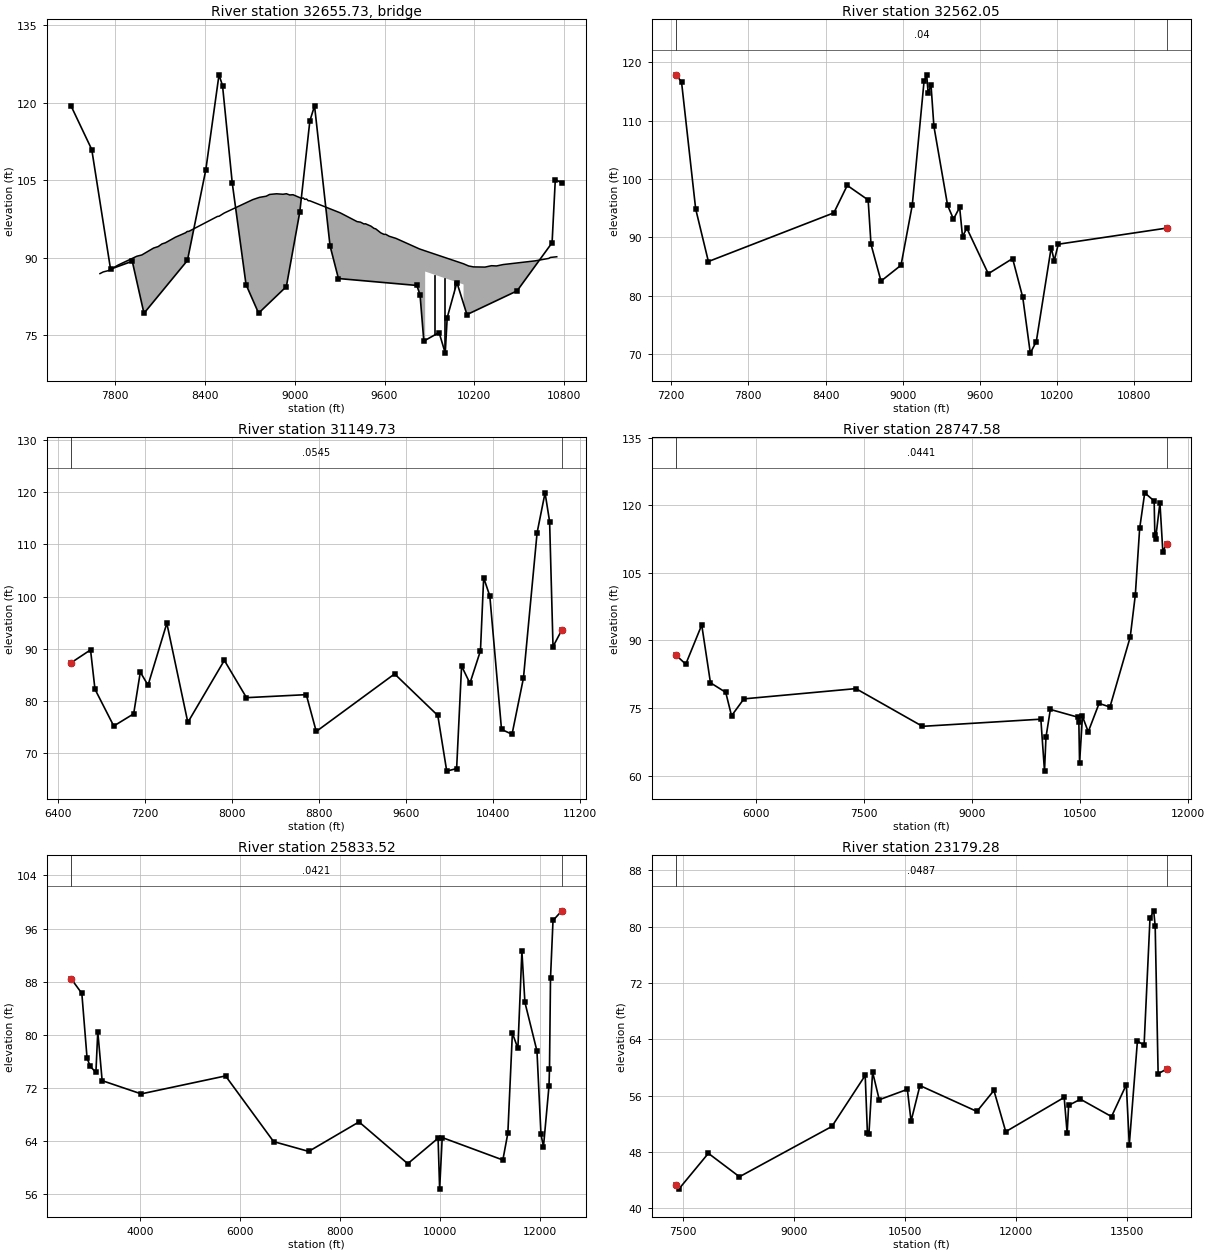
Type RM Length L Ch R = 3 ,32655.73,,,
BEGIN DESCRIPTION:
END DESCRIPTION:
Bridge Culvert--1,0,-1,-1, 0
Deck Dist Width WeirC Skew NumUp NumDn MinLoCord MaxHiCord MaxSubmerge Is_Ogee
51.200600,77.427700,2.6,0, 60, 60, , , 0.95, 0, 0,0,,
 7698.43 7719.90 7753.60 7820.99 7944.53 7978.23 8056.85 8087.94 8113.01 8135.47
 8202.86 8270.25 8281.48 8292.71 8483.31 8494.88 8528.57 8719.51 8764.43 8809.36
 8831.82 8878.68 8921.67 8944.57 8966.54 8988.50 9045.22 9056.45 9067.68 9078.91
 9090.15 9101.38 9304.21 9417.01 9439.57 9462.13 9473.41 9509.81 9529.81 9541.09
 9574.93 9596.26 9608.77 9631.33 9676.44 9833.27 9871.72 9871.7210128.2810128.28
10161.8510194.7110271.3810315.1910348.0510392.5810607.1410697.4810708.7710751.22
   86.95   87.27   87.52   88.62   90.31   90.56   91.90   92.19   92.70   92.91
   94.00   94.85   95.11   95.13   98.01   98.06   98.67  101.27  101.71  101.93
  102.27  102.40  102.31  102.41  102.17  102.22  101.52  101.59  101.31  101.39
  101.06  101.04   98.71   97.01   96.91   96.57   96.59   96.13   95.70   95.62
   94.84   94.55   94.55   94.18   93.77   91.73   91.35   91.35   88.85   88.85
   88.43   88.25   88.21   88.48   88.43   88.70   89.42   89.89   90.08   90.21
 -913.05 -912.73 -912.48 -911.38 -909.69 -909.44 -908.10 -907.81 -907.30 -907.09
 -906.00 -905.15 -904.89 -904.87 -901.99 -901.94 -901.33 -898.73 -898.29 -898.07
 -897.73 -897.60 -897.69 -897.59 -897.83 -897.78 -898.48 -898.41 -898.69 -898.61
 -898.94 -898.96 -901.29 -902.99 -903.09 -903.43 -903.41 -903.87 -904.30 -904.38
 -905.16 -905.45 -905.45 -905.82 -906.23 -908.27 -908.65   87.35   84.85 -911.15
 -911.57 -911.75 -911.79 -911.52 -911.57 -911.30 -910.58 -910.11 -909.92 -909.79
 7698.43 7719.90 7753.60 7820.99 7944.53 7978.23 8056.85 8087.94 8113.01 8135.47
 8202.86 8270.25 8281.48 8292.71 8483.31 8494.88 8528.57 8719.51 8764.43 8809.36
 8831.82 8878.68 8921.67 8944.57 8966.54 8988.50 9045.22 9056.45 9067.68 9078.91
 9090.15 9101.38 9304.21 9417.01 9439.57 9462.13 9473.41 9509.81 9529.81 9541.09
 9574.93 9596.26 9608.77 9631.33 9676.44 9833.27 9871.72 9871.7210128.2810128.28
10161.8510194.7110271.3810315.1910348.0510392.5810607.1410697.4810708.7710751.22
   86.95   87.27   87.52   88.62   90.31   90.56   91.90   92.19   92.70   92.91
   94.00   94.85   95.11   95.13   98.01   98.06   98.67  101.27  101.71  101.93
  102.27  102.40  102.31  102.41  102.17  102.22  101.52  101.59  101.31  101.39
  101.06  101.04   98.71   97.01   96.91   96.57   96.59   96.13   95.70   95.62
   94.84   94.55   94.55   94.18   93.77   91.73   91.35   91.35   88.85   88.85
   88.43   88.25   88.21   88.48   88.43   88.70   89.42   89.89   90.08   90.21
 -913.05 -912.73 -912.48 -911.38 -909.69 -909.44 -908.10 -907.81 -907.30 -907.09
 -906.00 -905.15 -904.89 -904.87 -901.99 -901.94 -901.33 -898.73 -898.29 -898.07
 -897.73 -897.60 -897.69 -897.59 -897.83 -897.78 -898.48 -898.41 -898.69 -898.61
 -898.94 -898.96 -901.29 -902.99 -903.09 -903.43 -903.41 -903.87 -904.30 -904.38
 -905.16 -905.45 -905.45 -905.82 -906.23 -908.27 -908.65   87.35   84.85 -911.15
 -911.57 -911.75 -911.79 -911.52 -911.57 -911.30 -910.58 -910.11 -909.92 -909.79
Pier Skew, UpSta & Num, DnSta & Num=  ,9934.86, 2 ,9934.86, 2 , 0 , 0 , 0 ,,
    4.00    4.00
 -909.27   90.73
    4.00    4.00
 -909.27   90.73
Pier Skew, UpSta & Num, DnSta & Num=  ,10000.00, 2 ,10000.00, 2 , 0 , 0 , 0 ,,
    4.00    4.00
 -909.91   90.09
    4.00    4.00
 -909.91   90.09
Pier Skew, UpSta & Num, DnSta & Num=  ,10065.14, 2 ,10065.14, 2 , 0 , 0 , 0 ,,
    4.00    4.00
 -910.55   89.45
    4.00    4.00
 -910.55   89.45
BR Coef=-1 , 0 , 0 ,, 0 ,,,0.8,0,1,0,
WSPro=,,,, 1 ,,,, 0 ,,,, 0 ,,,,-1 ,-1 ,-1 , 0 , 0 , 0 , 0 , 0
BC Design=,, 0 ,, 0 ,,,,,,

Type RM Length L Ch R = 1 ,32562.05,1412.328300,1412.328300,1412.328300
XS GIS Cut Line= 6
429273.807602197761500.065713152428862.349268913761312.565713152
426865.790911973762280.627553821426568.152022958762456.321998239
426258.985356271762585.349776059425844.836466581762787.614257872
#Sta/Elev= 30
7237.737117.82987280.384116.61737390.27794.875957489.18185.866248464.46394.19935
8568.58498.895998731.03696.403818753.25188.813128831.00182.514648986.50285.22908
9074.05695.52944 9165.96116.81299186.432 117.7179197.539114.66619219.773 116.098
9242.027 109.0389348.70195.479689394.30593.131039442.31695.135039464.571  90.142
9497.95291.57496 9664.8683.777229854.02186.375179933.05579.70798 9991.4470.18061
10038.1572.1691610153.8688.2512210177.6485.9992210208.8788.8275911051.2891.58754
#Mann= 3 , 0 , 0
7237.737    0.04       07237.737    0.04       011051.28    0.04       0
#XS Ineff= 2 , 0
       0 9883.76        10140.85       0
Bank Sta=7237.737,11051.28
Exp/Cntr=0.3,0.1

Type RM Length L Ch R = 1 ,31149.73,2402.150000,2402.150000,2402.150000
XS GIS Cut Line= 6
428839.934733361761269.828003749426514.880256176761705.111104965
425846.477478296761913.444438323425612.102478296762121.777771652
425499.255256087 762330.11110498425204.116367191763172.124993861
#Sta/Elev= 30
6519.59487.318486697.45389.771146738.12182.239916910.96375.183567093.97177.51709
7154.97485.505597226.14483.005417398.98594.872817592.161  75.8767927.75787.76753
8131.41380.615858681.28581.19341 8772.9374.139039493.44685.166219890.70277.19882
9972.80566.5382710063.7967.0302710109.2886.6796510186.1183.3763410282.9189.60232
10312.42103.604710368.95 100.093 10476.574.5353210573.2973.6003910678.2284.37705
10803.72112.227410876.93119.869210918.76114.364510950.1390.3926611030.7993.58855
#Mann= 3 , 0 , 0
6519.594  0.0545       06519.594  0.0545       011030.79  0.0545       0
#XS Ineff= 2 , 0
       08676.415        10265.52       0
Bank Sta=6519.594,11030.79
Exp/Cntr=0.3,0.1

Type RM Length L Ch R = 1 ,28747.58,2914.057400,2914.057400,2914.057400
XS GIS Cut Line= 6
429038.387162703761216.385838075  426254.4635894760819.694438323
425056.546922743760993.305549428424761.408033848761271.083327189
424553.074700505761791.916660532424318.699700534  763597.4722161
#Sta/Elev= 30
4883.77786.738885018.51184.733855240.73393.437355361.946 80.61735574.06778.49198
5654.87573.300155826.59277.045997382.14879.321368307.25470.956299951.68372.54485
10002.5461.0242410022.8968.5410910083.9274.7004510469.5572.97109 10479.671.99849
10489.6462.8286310529.8173.1626210610.1669.7458510760.8176.0414510911.7475.24447
11193.5390.7772211263.98100.056511324.36114.833411394.81122.736411525.64120.9311
 11535.7113.345911545.76112.533511606.15120.5253 11646.4109.673911699.21111.4721
#Mann= 3 , 0 , 0
4883.777  0.0441       04883.777  0.0441       011699.21  0.0441       0
#XS Ineff= 2 , 0
       07622.285        10537.33       0
Bank Sta=4883.777,11699.21
Exp/Cntr=0.3,0.1

Type RM Length L Ch R = 1 ,25833.52,2654.241500,2654.241500,2654.241500
XS GIS Cut Line= 6
429229.394734641761005.285878551425658.109422773759954.243049428
  424434.1510894760188.618049428423314.359422773760787.576382741
422767.484422743761516.743049428422819.567756087764159.972216085
#Sta/Elev= 30
2622.47388.426952835.53686.225652939.77776.505073002.32175.255843116.98674.32623
3154.77880.459263242.07573.093974023.88171.100825712.58273.80492 6674.1963.91624
7376.72762.439148384.28866.880239359.75760.588269966.93364.430059997.92456.76079
10049.5864.5272511263.4761.1477711363.6365.1866811454.0280.2498911564.5177.94964
11644.8692.5697511705.1384.8832911946.19 77.556912026.5465.0052612076.7663.15025
12187.2572.2862612197.2974.8633812217.3888.53404 12267.697.2062512443.3598.66105
#Mann= 3 , 0 , 0
2622.473  0.0421       02622.473  0.0421       012443.35  0.0421       0
#XS Ineff= 2 , 0
       06198.138        11213.46       0
Bank Sta=2622.473,12443.35
Exp/Cntr=0.3,0.1

Type RM Length L Ch R = 1 ,23179.28,3473.717800,3473.717800,3473.717800
XS GIS Cut Line= 2
421439.359422743758317.958327204421630.331644952764949.902771637
#Sta/Elev= 30
7402.15743.334737439.21442.73294 7839.3847.818348259.554 44.48959510.07251.63774
9960.25858.878529990.27150.6890410010.2850.51632 10060.359.3556910150.3455.42438
10530.4956.9035610580.5252.3833210700.5757.4390411470.8853.7636511700.9856.74636
11861.0550.8921312651.3755.7549912691.3950.66969 12711.454.6297412871.4655.49925
13291.6453.0348613491.7257.5651313531.7449.0255513641.7863.7635213731.8263.16181
13811.85 81.172813861.8782.2524713881.8880.10225 13921.959.1188914036.85  59.783
#Mann= 3 , 0 , 0
7402.157  0.0487       07402.157  0.0487       014036.85  0.0487       0
#XS Ineff= 2 , 0
       08292.309         12104.8       0
Bank Sta=7402.157,14036.85
Exp/Cntr=0.3,0.1

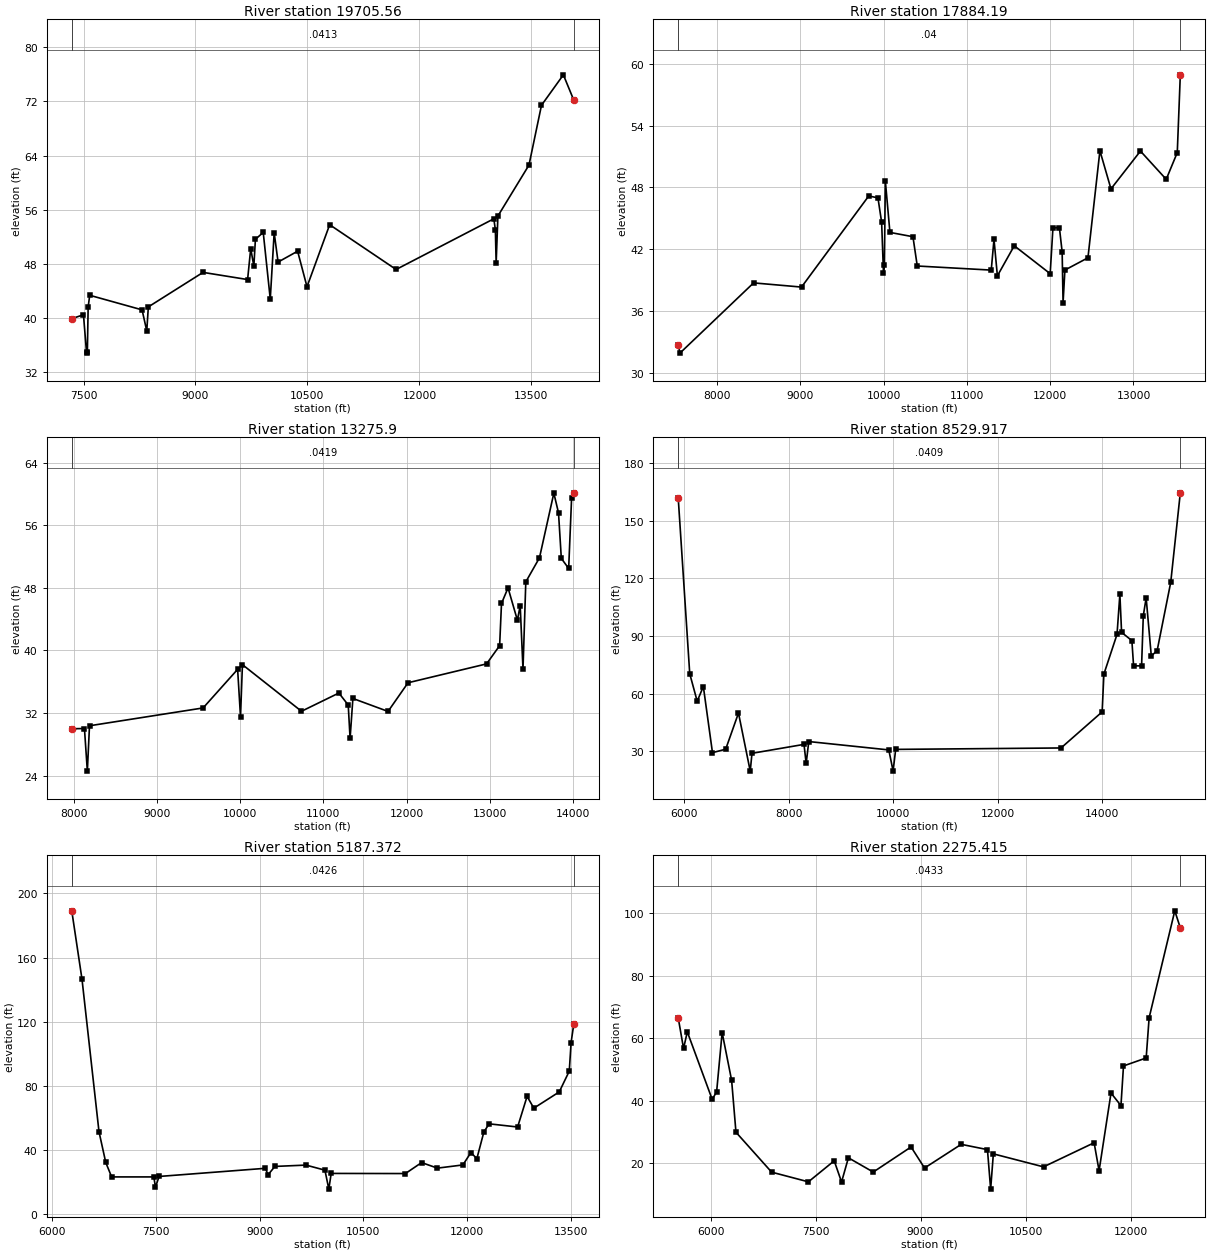
Type RM Length L Ch R = 1 ,19705.56,1821.368600,1821.368600,1821.368600
XS GIS Cut Line= 2
418800.470533848759255.458327204420796.998311639765679.069438308
#Sta/Elev= 30
7342.62939.932247499.227 40.50497541.11534.845147551.58735.058627562.05941.63272
7583.00243.380558284.61941.22793 8347.4538.117378368.39441.666399101.42646.75879
9698.32345.70035 9740.21 50.26959782.09847.672129803.04251.639489907.76152.65931
10002.0142.8275410054.3752.6170810106.7348.2824110368.5249.8834110494.1944.63917
10797.8753.7919411687.9847.1872612996.9754.6651313017.9153.0600713028.3848.14805
13051.8655.07583 13468.262.5922413635.7571.4171513928.96 75.908614069.36 72.1499
#Mann= 3 , 0 , 0
7342.629  0.0413       07342.629  0.0413       014069.36  0.0413       0
#XS Ineff= 2 , 0
       08276.288        10763.52       0
Bank Sta=7342.629,14069.36
Exp/Cntr=0.3,0.1

Type RM Length L Ch R = 1 ,17884.19,4608.287700,4608.287700,4608.287700
XS GIS Cut Line= 2
417081.720533878760366.569438323419651.164978325765817.958327189
#Sta/Elev= 30
7535.84432.715117556.21931.91429 8440.6338.732019015.49738.325329822.521 47.1672
9933.07246.986069977.29344.613539999.40339.7017710010.4640.4656510021.5148.65715
10076.7943.6309710353.1743.2127510405.0240.3702811292.8539.9731111326.0242.95424
11366.6739.4141311569.2342.3352512000.3839.6250712033.5544.0702512110.93 44.1002
 12144.141.7417912155.1536.8199512177.2639.9788412453.6441.1662712597.3651.56045
12730.0247.8543913083.7851.5267413393.33 48.783613525.9951.3815213562.4358.92655
#Mann= 3 , 0 , 0
7535.844    0.04       07535.844    0.04       013562.43    0.04       0
#XS Ineff= 2 , 0
       08329.165        10895.67       0
Bank Sta=7535.844,13562.43
Exp/Cntr=0.3,0.1

Type RM Length L Ch R = 1 , 13275.9,4745.985800,4745.985800,4745.985800
XS GIS Cut Line= 4
414759.671922743761612.229160547415616.876783848763120.475688308
416029.203172743763836.621521652417613.404561669766929.069438308
#Sta/Elev= 30
7974.55929.990888127.00930.020938161.78224.575588187.72330.371529553.55432.65032
9968.46137.5834710003.0831.5115610026.1638.1823410736.1732.22534 11185.634.55631
11297.9633.0233811320.4328.7616911354.1433.86085 11776.732.2041112017.0535.86909
12961.0838.2793713118.1640.6104513140.6346.0046613219.2847.9963713331.6443.86372
13365.3445.7174413399.0537.6064413432.7648.7590213597.1351.8396713769.8360.10028
13826.0157.5813213859.72  51.76313948.0650.4754413983.3159.4725514010.3660.14012
#Mann= 3 , 0 , 0
7974.559  0.0419       07974.559  0.0419       014010.36  0.0419       0
#XS Ineff= 2 , 0
       08817.164        11865.87       0
Bank Sta=7974.559,14010.36
Exp/Cntr=0.3,0.1

Type RM Length L Ch R = 1 ,8529.917,3342.544900,3342.544900,3342.544900
XS GIS Cut Line= 6
410311.685776561761836.937809885411149.654737204762347.113809288
  411926.5016976762685.120402262412868.028892875763373.074086457
414805.528892875765623.074086457416273.726571262768952.879029289
#Sta/Elev= 30
5888.067161.62666108.06770.320936250.61656.013456368.30263.665166542.92829.25866
6795.82231.046337040.65449.876157265.26119.643937298.831 28.91328293.97633.55831
 8335.2723.61353 8384.8135.033339915.84230.677269998.05619.7431110047.8130.95149
 13210.531.6967613997.38 50.486614030.1770.1144514281.5390.7803214336.18 111.638
14368.9791.8437114565.6987.5559714598.4774.4194914751.4874.4137414784.27100.4912
14838.91109.789314937.2779.5348115049.3382.3928615308.85117.844215492.33164.4461
#Mann= 3 , 0 , 0
5888.067  0.0409       05888.067  0.0409       015492.33  0.0409       0
#XS Ineff= 2 , 0
       08725.714        12174.29       0
Bank Sta=5888.067,15492.33
Exp/Cntr=0.3,0.1

Type RM Length L Ch R = 1 ,5187.372,2911.957600,2911.957600,2911.957600
XS GIS Cut Line= 6
409242.491775781763089.252713516410651.946587533764092.528877184
411280.399399161 764678.11651364411911.563815892765450.646115974
412812.970965236  767078.9043625413954.282126814768485.150271118
#Sta/Elev= 30
6279.861189.1687 6428.33146.41416674.00551.506186771.63832.361166857.06623.33554
7467.27323.333627491.68117.019227543.74623.62449 9083.47 28.70659120.95124.63922
9220.20829.873679670.22530.70496 9944.5727.5484910001.0915.72698 10035.225.51365
11109.5825.4307411344.3732.2714711572.9428.8092611941.8430.8011112058.2738.53145
12143.9534.7053712245.6151.3539312321.85 56.421112734.1654.4459312871.11 73.5119
12968.88 66.190913336.6976.3072713481.9189.2737513508.31107.065813548.12118.8925
#Mann= 3 , 0 , 0
6279.861  0.0426       06279.861  0.0426       013548.12  0.0426       0
#XS Ineff= 2 , 0
       08117.279                       0
Bank Sta=6279.861,13548.12
Exp/Cntr=0.3,0.1

Type RM Length L Ch R = 1 ,2275.415,1747.165900,1747.165900,1747.165900
XS GIS Cut Line= 6
407217.218871057763371.079804078409739.898614198765514.763550028
410407.424202412766122.108711138411073.956461608766815.006963059
 412278.26802808768010.968960732412382.434694737768292.218960717
#Sta/Elev= 30
5539.02866.489465614.85356.698835668.62562.028356023.81340.403596087.27742.79626
6166.01461.804096301.78746.469826363.55829.884026873.17617.100517398.23713.99988
7767.00520.732977871.98813.945887969.62621.695018324.81417.130418864.88325.16632
9057.40318.426429581.23126.007499955.94724.3121610001.68 11.664710040.1922.95637
10757.01 18.794111479.6326.5121311550.6217.55631   1172142.4321511862.99 38.4034
11899.2851.1114512223.2753.6642812265.5366.5373512631.93100.778812710.92 95.3227
#Mann= 3 , 0 , 0
5539.028  0.0433       05539.028  0.0433       012710.92  0.0433       0
#XS Ineff= 2 , 0
       07986.384                       0
Bank Sta=5539.028,12710.92
Exp/Cntr=0.3,0.1

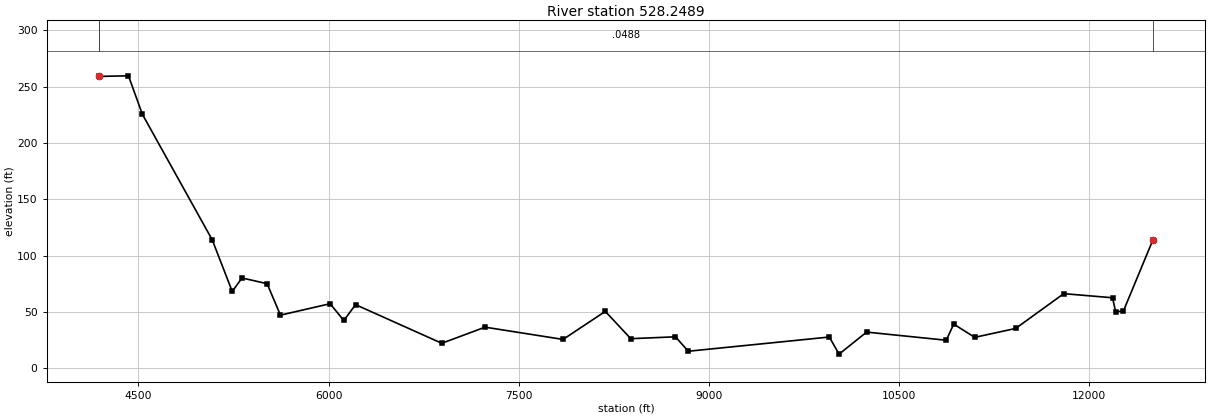
Type RM Length L Ch R = 1 ,528.2489,0.000000,0.000000,0.000000
XS GIS Cut Line= 6
405386.391596168763486.191358969408294.586114109765957.471883342
409188.010950744766789.318500534409833.511531711767473.678666294
410449.805412769768472.193955719411109.503797263769422.989728183
#Sta/Elev= 30
 4191.28259.00554421.085259.49824530.649225.4069 5081.81113.93975239.56268.19145
5316.77780.117595514.86575.036015619.84847.12546 6011.71 57.27246119.81142.38878
6212.46856.435946892.767 22.15647233.96236.462967849.42225.581328182.472 50.4485
8383.52726.247488735.56727.897258837.53315.099689949.86427.7064710026.4212.53105
 10243.832.0761110872.1424.8612110931.1139.1837811096.4227.4145111419.2835.30897
11799.0766.1961412183.5662.5497512208.2950.1270212269.7350.8334212500.93113.5741
#Mann= 3 , 0 , 0
 4191.28  0.0488       0 4191.28  0.0488       012500.93  0.0488       0
#XS Ineff= 2 , 0
       07394.331                       0
Bank Sta=4191.28,12500.93
Exp/Cntr=0.3,0.1